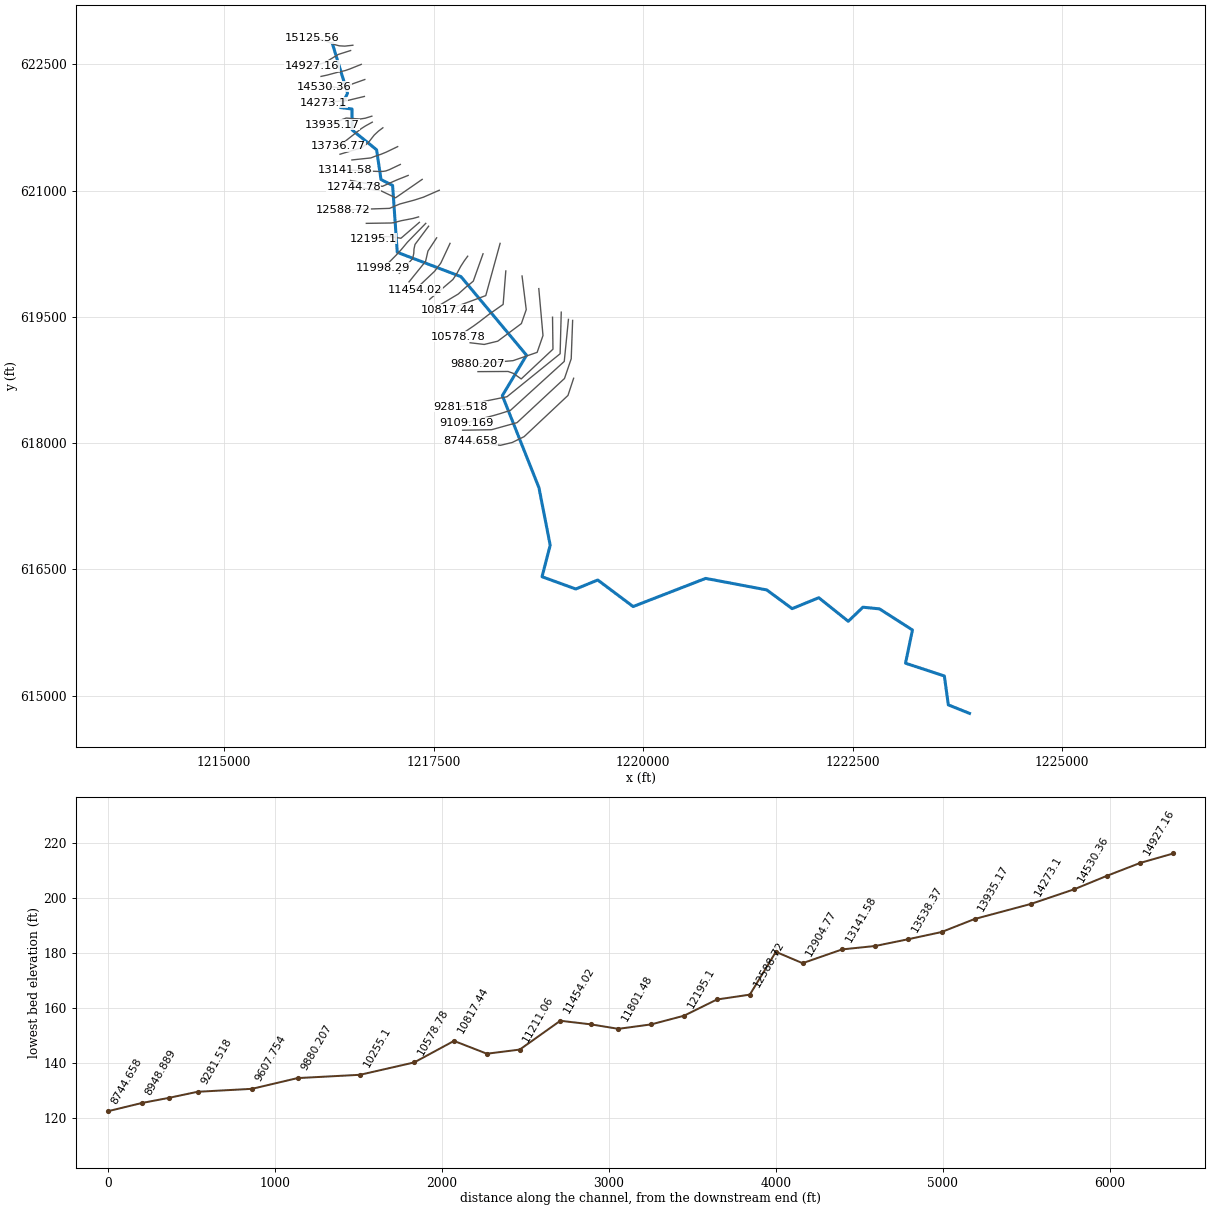
--- 241_ras.prj (project) ---

Proj Title=241
Current Plan=p01
Default Exp/Contr=0.3,0.1
English Units
Geom File=g01
Flow File=f01
Plan File=p01
Y Axis Title=Elevation
X Axis Title(PF)=Main Channel Distance
X Axis Title(XS)=Station
BEGIN DESCRIPTION:
RFD model 241 exported to HEC-RAS
END DESCRIPTION:

--- 241_ras.p01 (plan) ---

Plan Title=Plan 01
Program Version=4.10
Short Identifier=Plan 01
Geom File=g01
Flow File=f01
Subcritical Flow
Calc Critical at every XS
Secant Critical Depth

--- 241_ras.f01 (steady flow) ---

Flow Title=Flow 01
Program Version=5.01
Number of Profiles= 5
Profile Names=10yr,25yr,50yr,100yr,500yr
River Rch & RM=241,60,15125.56
  844.26 1130.09 1382.97 1657.52 2257.16
River Rch & RM=241,60,14927.16
  863.47 1159.61 1420.15 1707.76 2335.52
River Rch & RM=241,60,14728.76
  866.02 1163.53 1425.09 1714.45 2345.97
River Rch & RM=241,60,14530.36
  871.33 1171.71  1435.4 1728.41 2367.82
River Rch & RM=241,60, 14273.1
  872.33 1173.26 1437.35 1731.06 2371.97
River Rch & RM=241,60,13935.17
  901.71 1218.66 1494.62 1808.87 2494.21
River Rch & RM=241,60,13736.77
  904.33 1222.72 1499.74 1815.85 2505.22
River Rch & RM=241,60,13538.37
  907.18 1227.13 1505.31 1823.44 2517.18
River Rch & RM=241,60,13339.98
  913.53 1236.99 1517.75 1840.41 2543.97
River Rch & RM=241,60,13141.58
  921.67 1249.62  1533.7 1862.19 2578.42
River Rch & RM=241,60,12904.77
  924.66 1254.28 1539.58 1870.22 2591.14
River Rch & RM=241,60,12744.78
  929.92 1262.46 1549.92 1884.36 2613.54
River Rch & RM=241,60,12588.72
   932.2    1266 1554.39 1890.48 2623.23
River Rch & RM=241,60,12391.91
  934.01 1268.82 1557.95 1895.36 2630.98
River Rch & RM=241,60, 12195.1
  1047.8 1447.53 1784.17  2207.8 3132.27
River Rch & RM=241,60,11998.29
 1050.83 1452.32 1790.26 2216.28 3146.01
River Rch & RM=241,60,11801.48
 1062.07 1470.14 1812.86 2247.79 3197.18
River Rch & RM=241,60,11636.29
 1064.48 1473.96 1817.71 2254.56  3208.2
River Rch & RM=241,60,11454.02
 1075.14 1490.89 1839.19 2284.57 3257.04
River Rch & RM=241,60,11211.06
 1077.68 1494.94 1844.33 2291.76 3268.76
River Rch & RM=241,60,11014.25
 1080.77 1499.84 1850.55 2300.46 3282.95
River Rch & RM=241,60,10817.44
 1087.61 1510.72 1864.37  2319.8 3314.52
River Rch & RM=241,60,10578.78
 1090.29 1514.99 1869.79  2327.4 3326.93
River Rch & RM=241,60, 10255.1
  1095.8 1523.77 1880.95 2343.02 3352.47
River Rch & RM=241,60,9880.207
 1097.39 1526.31 1884.17 2347.54 3359.86
River Rch & RM=241,60,9607.754
 1100.39 1531.09 1890.24 2356.06 3373.79
River Rch & RM=241,60,9281.518
 1122.57 1566.51 1935.25 2419.29 3477.48
River Rch & RM=241,60,9109.169
 1124.44 1569.51 1939.06 2424.66  3486.3
River Rch & RM=241,60,8948.889
  1125.8 1571.69 1941.83 2428.55  3492.7
River Rch & RM=241,60,8744.658
 1128.01 1575.22 1946.32 2434.87 3503.08
River Rch & RM=241,60,8526.211
 1129.19 1577.11 1948.73 2438.26 3508.66
River Rch & RM=241,60,8162.182
  1132.9 1583.06 1956.28  2448.9 3526.17
River Rch & RM=241,60,7944.699
 1134.58 1585.75 1959.71 2453.73 3534.11
River Rch & RM=241,60, 7747.39
 1135.59 1587.36 1961.76 2456.62 3538.87
River Rch & RM=241,60,7422.812
 1148.72 1608.41 1988.53 2494.38 3601.12
River Rch & RM=241,60,7173.661
 1150.53 1611.32 1992.23  2499.6 3609.73
River Rch & RM=241,60,6665.675
 1290.25 1837.51 2280.55 2910.28 4295.19
River Rch & RM=241,60,6209.863
 1295.06 1845.37 2290.59 2924.69 4319.51
River Rch & RM=241,60,5837.243
 1320.98 1887.76 2344.75 3002.64 4451.33
River Rch & RM=241,60, 5427.65
 1355.26 1944.03 2416.69 3106.51 4627.76
River Rch & RM=241,60,5229.304
 1357.95 1948.44 2422.33 3114.67 4641.66
River Rch & RM=241,60,5030.958
 1360.75 1953.04 2428.22  3123.2 4656.18
River Rch & RM=241,60,4832.611
 1388.15 1998.18 2485.99 3206.95 4799.16
River Rch & RM=241,60,4634.265
 1390.24 2001.64 2490.41 3213.37 4810.14
River Rch & RM=241,60,4435.918
 1393.55 2007.11 2497.41 3223.54 4827.54
River Rch & RM=241,60,4237.572
 1399.29 2016.58 2509.55 3241.17 4857.73
River Rch & RM=241,60,4039.225
 1400.27 2018.19  2511.6 3244.16 4862.86
River Rch & RM=241,60,3840.879
 1401.36    2020 2513.92 3247.53 4868.63
River Rch & RM=241,60,3642.532
 1412.71 2038.76 2537.94 3282.47 4928.55
River Rch & RM=241,60,3444.186
 1460.07 2117.29 2638.59 3429.33 5181.37
River Rch & RM=241,60,3178.364
 1463.49 2122.97 2645.87 3439.99 5199.77
River Rch & RM=241,60,2849.146
 1465.76 2126.74 2650.71 3447.07 5212.01
River Rch & RM=241,60,2524.325
  1473.1 2138.96 2666.37    3470 5251.66
River Rch & RM=241,60,2254.107
 1478.93 2148.67 2678.83 3488.25 5283.24
River Rch & RM=241,60,1857.414
 1483.39  2156.1 2688.37 3502.23 5307.44
River Rch & RM=241,60,1460.721
 1484.06 2157.21 2689.79 3504.32 5311.07
Boundary for River Rch & Prof#=241,60,1
Up Type= 0
Dn Type= 2
Boundary for River Rch & Prof#=241,60,2
Up Type= 0
Dn Type= 2
Boundary for River Rch & Prof#=241,60,2
Up Type= 0
Dn Type= 2
Boundary for River Rch & Prof#=241,60,2
Up Type= 0
Dn Type= 2
Boundary for River Rch & Prof#=241,60,2
Up Type= 0
Dn Type= 2

--- 241_ras.g01 (geometry) ---

Geom Title=241
Program Version=4.10

River Reach=241,60
Reach XY= 30
1216292.81733865622748.7080303131216474.37588656622156.752523482
1216389.29894993621986.5986502921216527.15509719621970.055912614
1216529.93482229621720.0379366731216820.76806301621485.037998006
1216873.26803735621132.5381011661217011.60132778 621061.70478484
 1217067.4346216620267.538352311  1217827.434389 619978.37174952
1218609.10079792619045.0386706441218320.76753584618565.038821533
1218757.43404195617471.7058001461218891.60064912616788.372665763
1218794.10066709616414.2061130551219196.60054412616268.372811362
1219459.10046974616375.0394387541219880.76700285616060.039520115
1220745.76675725616394.206062511 1221474.0998717  616257.5394153
1221777.43310905 616035.039472611222095.24379149616164.684562176
1222446.91034624615884.6846350881222621.91029948616052.184580281
1222819.41024062616032.1845805351223212.68817028615781.454834655
1223129.74913225615386.8258960551223593.08232436615235.159260973
1223640.58230045614891.8260281981223893.08222303614790.992717505

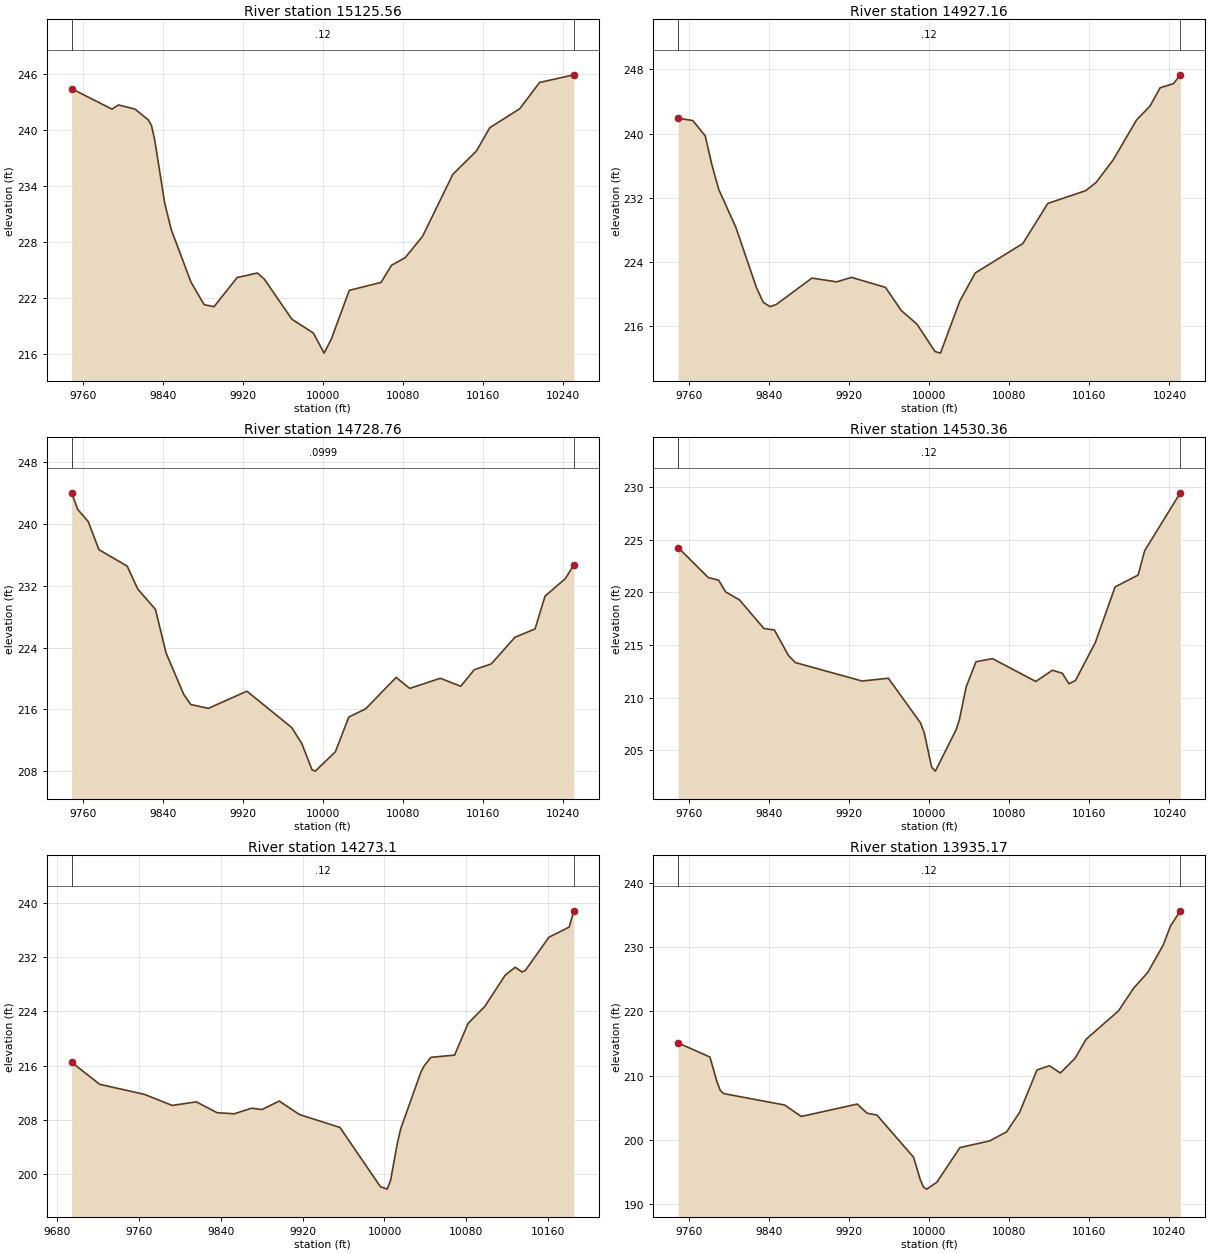
Type RM Length L Ch R = 1 ,15125.56,198.397700,198.397700,198.397700
XS GIS Cut Line= 6
1216537.70453145622727.1747514851216442.24445564 622716.63231883
1216375.41753547622720.1680760471216327.08586264622732.805147717
1216196.18357788622784.2137535661216050.48516442622809.106880409
#Sta/Elev= 30
9749.078244.45599789.361242.26959795.977242.71399812.436242.26929825.603 241.117
9828.895240.49659832.186238.89839842.061232.18259848.634229.32829868.319223.7125
9881.443221.28949891.334221.07149914.478224.20059934.619224.68349941.375224.0682
9969.169219.72599990.601218.253110001.37 216.09110008.55217.593310026.49222.8232
10058.29223.678810068.65225.510210082.46226.337710099.72228.622110130.02235.2748
10153.52237.769610166.94240.278910196.82242.305510216.67245.127110250.91245.9478
#Mann= 3 , 0 , 0
9749.078    0.12       09749.078    0.12       010250.91    0.12       0
#XS Ineff= 2 , 0
       09932.016                       0
Bank Sta=9749.078,10250.91
Exp/Cntr=0.3,0.1

Type RM Length L Ch R = 1 ,14927.16,198.397700,198.397700,198.397700
XS GIS Cut Line= 6
1216510.73456001622664.1657943271216363.60514856622617.674844421
1216235.72990795622540.0401281431216184.80390059622515.945582936
1216124.74726851622496.510595507 1216048.3095697622479.919119037
#Sta/Elev= 30
9749.074241.91299763.746241.61419776.137239.7159 9782.96  236.049789.782233.0043
9806.838228.29849827.305220.82249834.128218.9817 9840.95218.43629847.159218.7111
9882.805221.99589907.507221.52749922.305222.08639956.289220.83639972.055217.9614
9987.822216.246610005.75212.856110011.21212.6498 10030.5 219.11810045.93222.6239
10093.55226.301910118.48231.290810156.41232.886710166.76233.9105 10183.7236.6916
 10207.2241.693110220.63243.4217 10230.7245.693610244.13246.216110250.89247.3108
#Mann= 3 , 0 , 0
9749.074    0.12       09749.074    0.12       010250.89    0.12       0
#XS Ineff= 2 , 0
       09914.524                       0
Bank Sta=9749.074,10250.89
Exp/Cntr=0.3,0.1

Type RM Length L Ch R = 1 ,14728.76,198.397600,198.397600,198.397600
XS GIS Cut Line= 6
 1216637.9513053622499.8635018031216500.75965017622445.071856462
1216445.56110476622425.8695968911216361.29393224622407.300145936
1216232.28197946 622372.859019061216158.04700807622356.908743959
#Sta/Elev= 30
9749.024244.04189755.063 241.9039765.662240.3045 9776.26 236.6829804.523234.5521
9815.121 231.5769832.785 228.9489843.384223.29869861.048 217.9349868.113216.6216
9885.777216.12739924.172218.3496 9968.99213.6377 9979.16211.54469989.224208.1726
9992.566207.993810012.64210.500810026.05214.998210042.82216.055610073.38 220.134
10086.96218.707910117.52220.0222 10137.9218.983810151.48221.133910168.46221.8792
10192.03225.324410212.16226.410210222.23230.672510242.36232.914510250.97234.6914
#Mann= 3 , 0 , 0
9749.024  0.0999       09749.024  0.0999       010250.97  0.0999       0
#XS Ineff= 2 , 0
       09913.986        10090.77       0
Bank Sta=9749.024,10250.97
Exp/Cntr=0.3,0.1

Type RM Length L Ch R = 1 ,14530.36,257.263200,257.263200,257.263200
XS GIS Cut Line= 6
1216680.37954962622320.0465380241216528.83775417622266.525784894
1216420.71786488622217.6874048481216394.55307592622218.003431836
1216282.84220688622233.985858694  1216199.744819622235.834490792
#Sta/Elev= 30
9749.028224.24339779.096221.40439789.534 221.1489796.493220.03999810.411 219.275
9834.767216.56339845.205216.43139859.123214.03359866.082213.33799932.816 211.586
9959.106211.85179991.255207.61389994.965206.674710002.38203.414510006.05203.0417
10026.89206.984410030.25207.983510036.81 211.01510046.66213.413210063.18  213.71
10106.42211.541910123.03212.610410132.93212.321110139.53211.326410146.13211.6418
10165.94215.242610185.66220.510710208.65221.629210215.21223.940210250.83 229.432
#Mann= 3 , 0 , 0
9749.028    0.12       09749.028    0.12       010250.83    0.12       0
#XS Ineff= 2 , 0
       09940.802        10073.06       0
Bank Sta=9749.028,10250.83
Exp/Cntr=0.3,0.1

Type RM Length L Ch R = 1 , 14273.1,337.929800,337.929800,337.929800
XS GIS Cut Line= 3
1216675.31985086622118.9661938851216474.65923032622070.706044659
1216191.44835451622046.575970024
#Sta/Elev= 30
9694.394216.48649721.725213.23849765.592211.74659792.587210.11719816.208210.6417
9836.454209.04549853.326208.88429870.198209.70539880.321209.50769897.193 210.759
9917.036208.76329956.549206.86519996.061198.117510002.65197.761710005.94199.0157
10012.52204.479510015.82206.643810035.57215.033710038.87215.966810045.45 217.222
 10068.5217.542310081.67222.221710098.14224.752810117.89229.338610127.77 230.516
10134.36229.815910137.65230.0511 10160.7 234.94910180.45236.441910185.01238.8442
#Mann= 3 , 0 , 0
9694.394    0.12       09694.394    0.12       010185.01    0.12       0
#XS Ineff= 2 , 0
       0                               0
Bank Sta=9694.394,10185.01
Exp/Cntr=0.3,0.1

Type RM Length L Ch R = 1 ,13935.17,198.397700,198.397700,198.397700
XS GIS Cut Line= 6
1216764.21898816 621884.575202991216685.08861671621860.316991666
1216623.56235879621850.9948509041216458.53819462621862.171452432
1216409.41388371621844.6582562651216285.63240209621782.778435613
#Sta/Elev= 30
9749.059215.08599780.867212.88639787.784209.08159791.243207.65849794.702207.1798
9855.534205.3963  9872.1203.61549928.036205.54319937.898204.1285 9947.79203.8239
9984.346197.25639990.993193.78719994.316192.5758 9997.64192.275210007.59193.3465
10030.71198.756710060.38199.799110077.38 201.21810090.38204.264610107.68210.8648
10120.07211.531510131.07210.398110145.74212.693410156.75 215.65510189.13220.0853
10204.43223.665810218.48226.102710233.77  230.3410241.11233.337510250.93235.7013
#Mann= 3 , 0 , 0
9749.059    0.12       09749.059    0.12       010250.93    0.12       0
#XS Ineff= 2 , 0
       0                               0
Bank Sta=9749.059,10250.93
Exp/Cntr=0.3,0.1

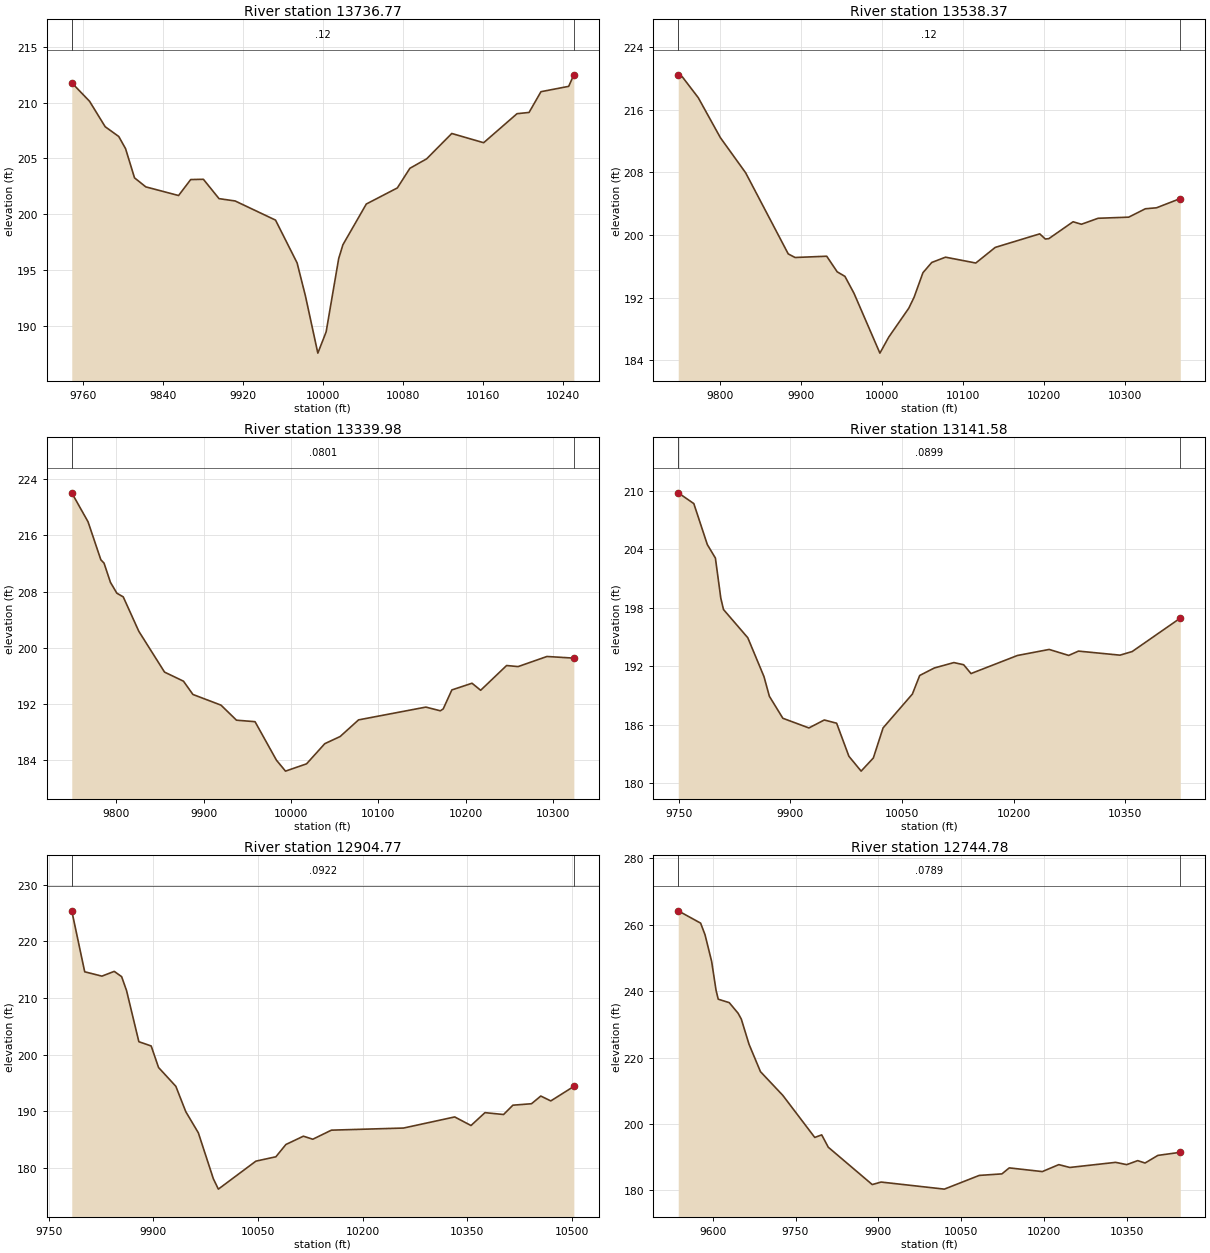
Type RM Length L Ch R = 1 ,13736.77,198.397700,198.397700,198.397700
XS GIS Cut Line= 6
1216769.28424464621813.4499457141216685.17514449621766.984733663
1216636.12721987 621735.421660711216451.13412313621590.760219069
1216402.95800582621555.5624570021216359.05043034621525.832638485
#Sta/Elev= 30
9749.035211.77249766.801210.11789782.456207.83329796.025206.9566 9802.81205.8672
 9811.78203.25029823.024202.44099855.815201.66569867.941203.09749880.642203.1203
9896.248201.38679912.355201.17729952.745199.46119974.312195.6237 9982.64192.6638
9995.043187.534810003.34189.4388 10015.9196.015810020.09 197.24810043.51200.9037
10074.52202.346310087.08204.106310103.83204.954510128.95207.227810160.82206.3996
10194.19 209.00310206.22209.1144 10218.1 210.97410245.84211.453410250.99212.4867
#Mann= 3 , 0 , 0
9749.035    0.12       09749.035    0.12       010250.99    0.12       0
#XS Ineff= 2 , 0
       0                               0
Bank Sta=9749.035,10250.99
Exp/Cntr=0.3,0.1

Type RM Length L Ch R = 1 ,13538.37,198.397700,198.397700,198.397700
XS GIS Cut Line= 6
1216895.62361618621746.498296054 1216843.6888413621707.455375607
1216792.42607842621659.9732937951216720.30591003621567.991069221
1216644.13018149621510.4083332871216384.43471643621432.499693781
#Sta/Elev= 30
9749.086220.4706 9754.21220.20369773.758 217.5529801.058212.43859832.168207.9577
9884.594197.60699893.037197.14719932.008197.3107 9944.94195.31659954.455194.7377
9965.598192.58199997.523184.937410008.45186.985410033.13190.675110039.68192.0838
10050.56195.207110061.44196.516410078.37197.188810115.65196.441710139.62198.4361
10194.43200.166110201.28199.510410205.63199.554910235.53201.710610245.81201.3914
10266.36202.156210304.04202.298210324.59203.368610338.29203.493110367.62204.6746
#Mann= 3 , 0 , 0
9749.086    0.12       09749.086    0.12       010367.62    0.12       0
#XS Ineff= 2 , 0
       0                               0
Bank Sta=9749.086,10367.62
Exp/Cntr=0.3,0.1

Type RM Length L Ch R = 1 ,13339.98,198.397600,198.397600,198.397600
XS GIS Cut Line= 6
1217072.25651193621523.0454594941216934.26553568621456.884036541
1216870.04017505 621430.760168211216812.96878052  621412.1628948
1216752.26474699621388.6349981131216526.26839352621364.579341382
#Sta/Elev= 30
9749.024222.05269767.658217.93269782.312212.53069785.976212.05699793.303 209.321
9800.631207.78059807.958207.25479825.767202.36419855.248196.55539876.904195.2656
9887.732193.37599919.877191.85759937.586189.71919958.838189.50429983.349184.0276
9993.731182.473410017.84183.510910038.67186.375810056.26187.393810077.37189.7625
10154.45191.580410170.95191.053310174.25191.317810184.15194.020910207.24194.9737
10217.14 193.97210246.84197.491710260.03 197.34110293.03198.778610323.82 198.544
#Mann= 3 , 0 , 0
9749.024  0.0801       09749.024  0.0801       010323.82  0.0801       0
#XS Ineff= 2 , 0
       0                               0
Bank Sta=9749.024,10323.82
Exp/Cntr=0.3,0.1

Type RM Length L Ch R = 1 ,13141.58,236.809400,236.809400,236.809400
XS GIS Cut Line= 6
 1217104.0514892621311.1957722141216972.63610129621249.147493828
1216930.03259362621233.7906522811216896.32396747621228.522508234
1216815.97997586621228.7790704111216446.36209655621246.717553422
#Sta/Elev= 30
9749.113209.80439770.073 208.6999788.214204.49499799.098203.10129806.355 198.993
9809.983197.82139842.636194.92539864.405190.93559871.661188.91629889.802 186.655
9924.857185.66119945.492186.47929962.095186.1483 9978.64  182.759995.045181.2275
10011.45182.575510024.57 185.66610063.96  189.1410073.81191.050410093.52  191.82
 10119.8192.373710132.94192.152310142.79191.2449 10205.2193.1012 10247.9193.7222
10274.18193.109410287.32193.550810343.16 193.13610359.58193.508910424.25196.9405
#Mann= 3 , 0 , 0
9749.113  0.0899       09749.113  0.0899       010424.25  0.0899       0
#XS Ineff= 2 , 0
       0                               0
Bank Sta=9749.113,10424.25
Exp/Cntr=0.3,0.1

Type RM Length L Ch R = 1 ,12904.77,159.986000,159.986000,159.986000
XS GIS Cut Line= 4
1217197.48128775621180.7948584411217061.64058292621126.858108014
1216889.84204453621050.9471259421216510.28713411621120.865135759
#Sta/Elev= 30
9782.941225.4038 9801.49214.6308  9826.2213.8637 9843.85 214.705 9854.44213.7712
  9861.5211.3073 9879.15 202.275  9896.8201.5255 9907.39197.71679932.148194.4019
9946.495189.8963 9964.43186.17849985.951178.06259993.124176.227610046.93 181.171
10075.62181.944310089.97184.112310115.08185.581310128.55185.044510155.24186.6477
10258.66 187.02110332.05188.9832 10355.4187.468610375.42 189.742 10402.1189.4114
10415.45 191.05910442.14191.316610455.48 192.677 10469.8191.813410502.86194.3769
#Mann= 3 , 0 , 0
9782.941  0.0922       09782.941  0.0922       010502.86  0.0922       0
#XS Ineff= 2 , 0
       0                10125.01       0
Bank Sta=9782.941,10502.86
Exp/Cntr=0.3,0.1

Type RM Length L Ch R = 1 ,12744.78,156.066400,156.066400,156.066400
XS GIS Cut Line= 4
1217364.53644776621133.7211700681217046.80712661620914.767803669
1216878.88800353620995.4348334071216546.34228918621048.115342617
#Sta/Elev= 30
9537.725264.22429578.258260.51329586.227257.0147 9598.18248.98689606.149240.3134
9610.134 237.5859630.056236.54949645.993233.37649651.882231.59219665.915223.9824
9686.573215.74949727.047208.59499784.865195.91599797.401196.69179809.354192.9635
9888.939181.7079 9904.98 182.46710019.42 180.33610082.65  184.4710123.66184.9281
10136.94186.737710196.73185.625410226.63187.720310246.56186.8663 10329.6188.4071
10349.54 187.71710369.47188.925710382.75188.2043   10406190.503910446.57191.4336
#Mann= 3 , 0 , 0
9537.725  0.0789       09537.725  0.0789       010446.57  0.0789       0
#XS Ineff= 2 , 0
       09942.757        10047.59       0
Bank Sta=9537.725,10446.57
Exp/Cntr=0.3,0.1

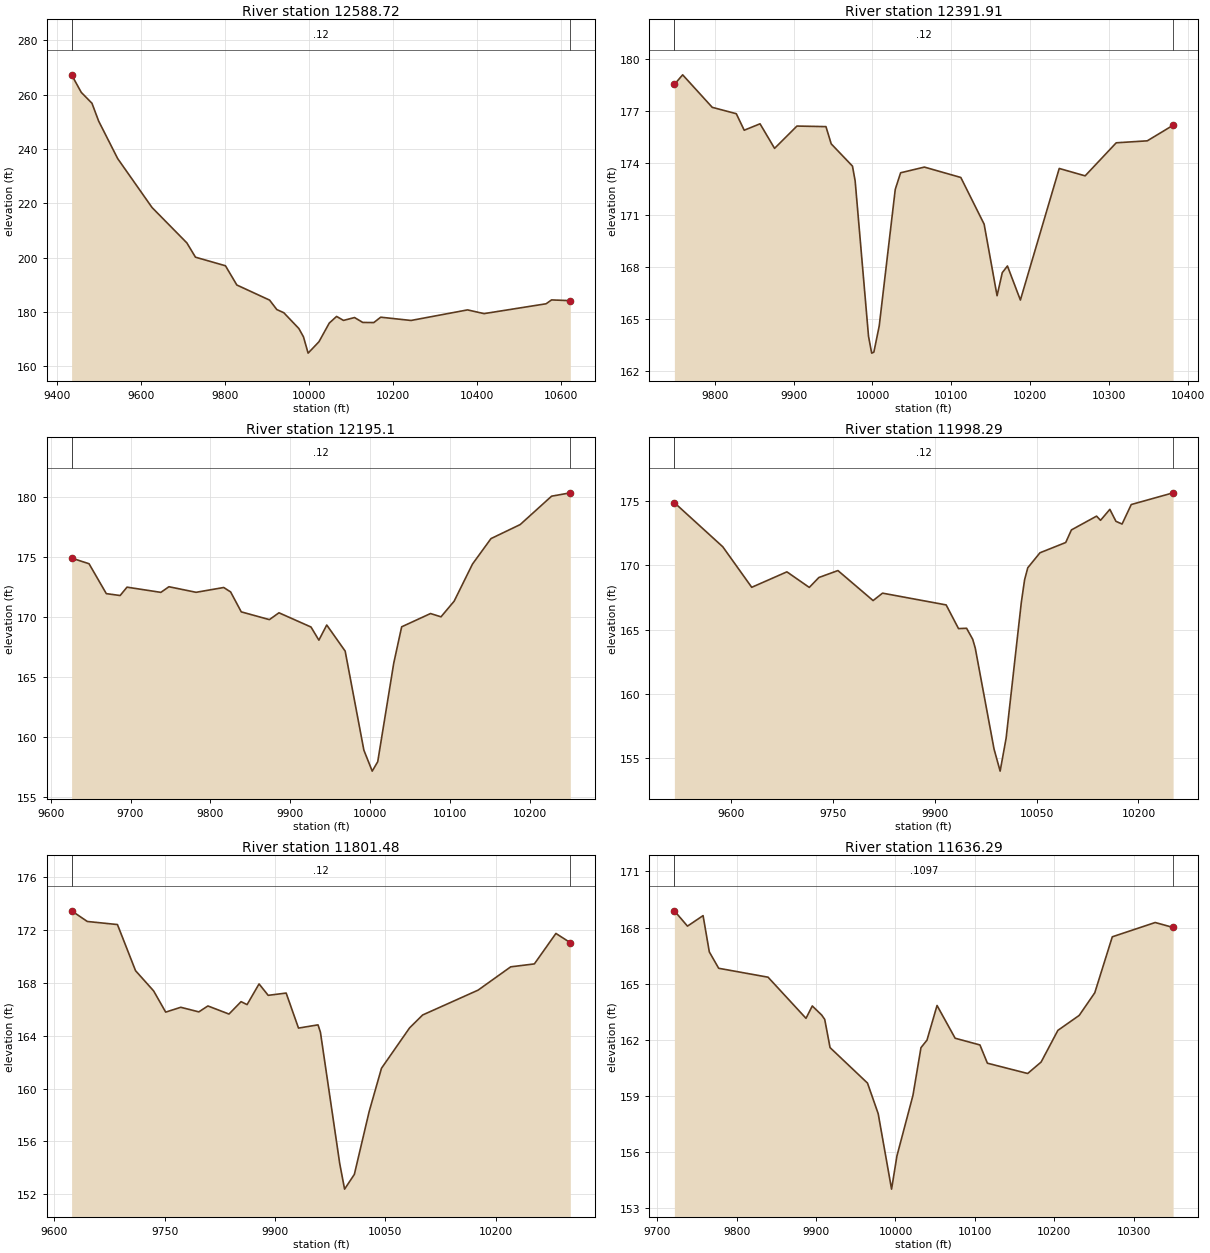
Type RM Length L Ch R = 1 ,12588.72,196.808800,196.808800,196.808800
XS GIS Cut Line= 6
 1217568.5050649621004.8462941941217381.01344797620922.967227668
1217273.31238154620888.394284174 1217097.2664935620841.240337268
1216975.84503049620789.5569803271216420.39255008620771.275086671
#Sta/Elev= 30
9433.722267.34819456.784260.87459482.235256.86959498.141250.30669543.478236.4823
9625.381218.44489708.281205.41429728.826200.14749800.236196.98319827.353189.8932
9905.425184.32569922.541180.85389939.231179.67489974.987173.87489986.018170.8141
9997.107 164.79510022.89168.972210047.48175.859910064.94178.319310081.41 176.849
10107.67177.907810127.37176.095610153.63 176.06210170.04178.034410242.26176.8312
10376.85180.724710416.24179.354110563.96  182.9810577.09184.403610621.74184.1281
#Mann= 3 , 0 , 0
9433.722    0.12       09433.722    0.12       010621.74    0.12       0
#XS Ineff= 2 , 0
       0                10091.93       0
Bank Sta=9433.722,10621.74
Exp/Cntr=0.3,0.1

Type RM Length L Ch R = 1 ,12391.91,196.808800,196.808800,196.808800
XS GIS Cut Line= 6
1217321.56061777620688.3319294011217257.51602748620670.166145265
1217116.59733039 620643.238707111217028.69633296620620.635533154
1216995.15750071620615.6925069091216698.06693193620611.462492809
#Sta/Elev= 30
9749.053178.51969759.536179.07159797.014177.19859827.492176.83099837.513175.8798
9857.554176.24979875.968174.83439904.317176.11979941.059176.08739947.739 175.094
9974.676173.81159978.063172.95719994.999164.0065    9999163.038110001.76163.0927
10008.54164.598410028.87172.471410035.65 173.428 10065.8173.756110111.93 173.158
10141.46170.467910157.86166.344310164.43 167.67210170.99168.059210187.39166.0964
10236.61173.677410269.42173.2516 10308.8175.154910348.17175.269210380.88176.1671
#Mann= 3 , 0 , 0
9749.053    0.12       09749.053    0.12       010380.88    0.12       0
#XS Ineff= 2 , 0
       0                10084.71       0
Bank Sta=9749.053,10380.88
Exp/Cntr=0.3,0.1

Type RM Length L Ch R = 1 , 12195.1,196.808800,196.808800,196.808800
XS GIS Cut Line= 6
 1217331.3243351620623.4484373481217111.34443203620434.450662464
1216999.61733577620452.0325014261216939.80723259620454.805724901
1216861.76797322620447.5548671491216780.79186248620431.052914954
#Sta/Elev= 30
9626.224174.91129648.068174.43899669.695 171.9479686.996171.79029695.647172.4864
9738.053172.05279748.122172.52299782.156172.05779816.759172.4581 9825.41172.0893
9838.743170.42769873.984169.78119885.966170.35089926.102169.1641 9935.96168.0698
9945.818 169.3339968.881167.15749992.325158.900510002.77 157.15310009.67157.9373
10029.76166.159910039.65169.182410075.81170.287810088.93170.014510105.37171.3158
10128.38174.412610151.52176.533710188.13177.704410227.43180.069610250.92180.3495
#Mann= 3 , 0 , 0
9626.224    0.12       09626.224    0.12       010250.92    0.12       0
#XS Ineff= 2 , 0
       09804.832                       0
Bank Sta=9626.224,10250.92
Exp/Cntr=0.3,0.1

Type RM Length L Ch R = 1 ,11998.29,196.808800,196.808800,196.808800
XS GIS Cut Line= 6
1217407.23531717620611.4624928091217188.92774385620387.858056009
 1217114.8816269620299.454283908 1217056.1015684620235.781233966
 1216973.0385882 620152.183664591216899.14668512620082.750306487
#Sta/Elev= 30
9517.256174.87039588.483171.44159631.044168.29169682.792169.49289715.722168.2831
9729.836169.05389757.862169.59269809.583167.2595 9823.49167.83659917.084 166.922
9935.258165.08069947.137 165.1059956.112164.25429959.881163.56549987.522155.7194
9996.496153.997610005.32156.569110027.66167.117810032.49168.877110037.15169.8092
 10055.1170.9763   10093 171.77510101.35172.753310138.35173.825310144.21173.5014
10157.89174.352410166.89173.4212 10175.9173.2105 10189.4174.727910250.98175.6379
#Mann= 3 , 0 , 0
9517.256    0.12       09517.256    0.12       010250.98    0.12       0
#XS Ineff= 2 , 0
       09774.092                       0
Bank Sta=9517.256,10250.98
Exp/Cntr=0.3,0.1

Type RM Length L Ch R = 1 ,11801.48,165.196200,165.196200,165.196200
XS GIS Cut Line= 6
 1217441.1954934620577.5023166241217279.12376432620360.964413594
1217266.87124912620306.4134540421217264.38506962620255.519188645
1217251.41803819620193.9520913361217091.60544428620018.158238083
#Sta/Elev= 30
 9623.58173.46889644.923172.66259685.903172.42929710.492168.9344 9735.08167.4022
9751.472165.79499771.962166.1607 9796.55165.81349808.844166.2613 9837.53165.6486
9853.923166.58719862.119166.3643 9878.39167.93089890.805 167.0669915.235167.2384
9932.001164.5857 9958.52164.82979961.805164.27399988.084154.30489994.654152.3845
10007.93153.501910028.05158.262210044.81161.540810082.99164.599710100.73165.5774
 10176.1167.459810220.44169.224910252.64169.447810281.91171.7555 10301.5171.0541
#Mann= 3 , 0 , 0
 9623.58    0.12       0 9623.58    0.12       0 10301.5    0.12       0
#XS Ineff= 2 , 0
       09892.302                       0
Bank Sta=9623.58,10301.5
Exp/Cntr=0.3,0.1

Type RM Length L Ch R = 1 ,11636.29,182.264500,182.264500,182.264500
XS GIS Cut Line= 4
1217537.08304971620439.6639544221217433.20486367620281.849017978
1217405.23765978620159.9919151511217207.46957487619916.277709514
#Sta/Elev= 30
9721.697168.89419738.174168.07569757.813168.63839765.668166.69939777.452 165.823
9839.641165.34559887.379163.14769895.285163.80839907.068163.32529910.944163.0903
9917.676161.58199964.802159.68559978.267158.05039995.097154.016910001.83155.7879
10022.03159.031810032.12161.579310039.67161.980110052.35163.834310075.12162.0837
10106.36161.723210115.73160.748910166.43160.198110183.33160.808810204.45162.5029
10231.32163.304310250.93164.515110272.97167.505910326.98168.269310349.52168.0052
#Mann= 3 , 0 , 0
9721.697  0.1097       09721.697  0.1097       010349.52  0.1097       0
#XS Ineff= 2 , 0
       09910.274                       0
Bank Sta=9721.697,10349.52
Exp/Cntr=0.3,0.1

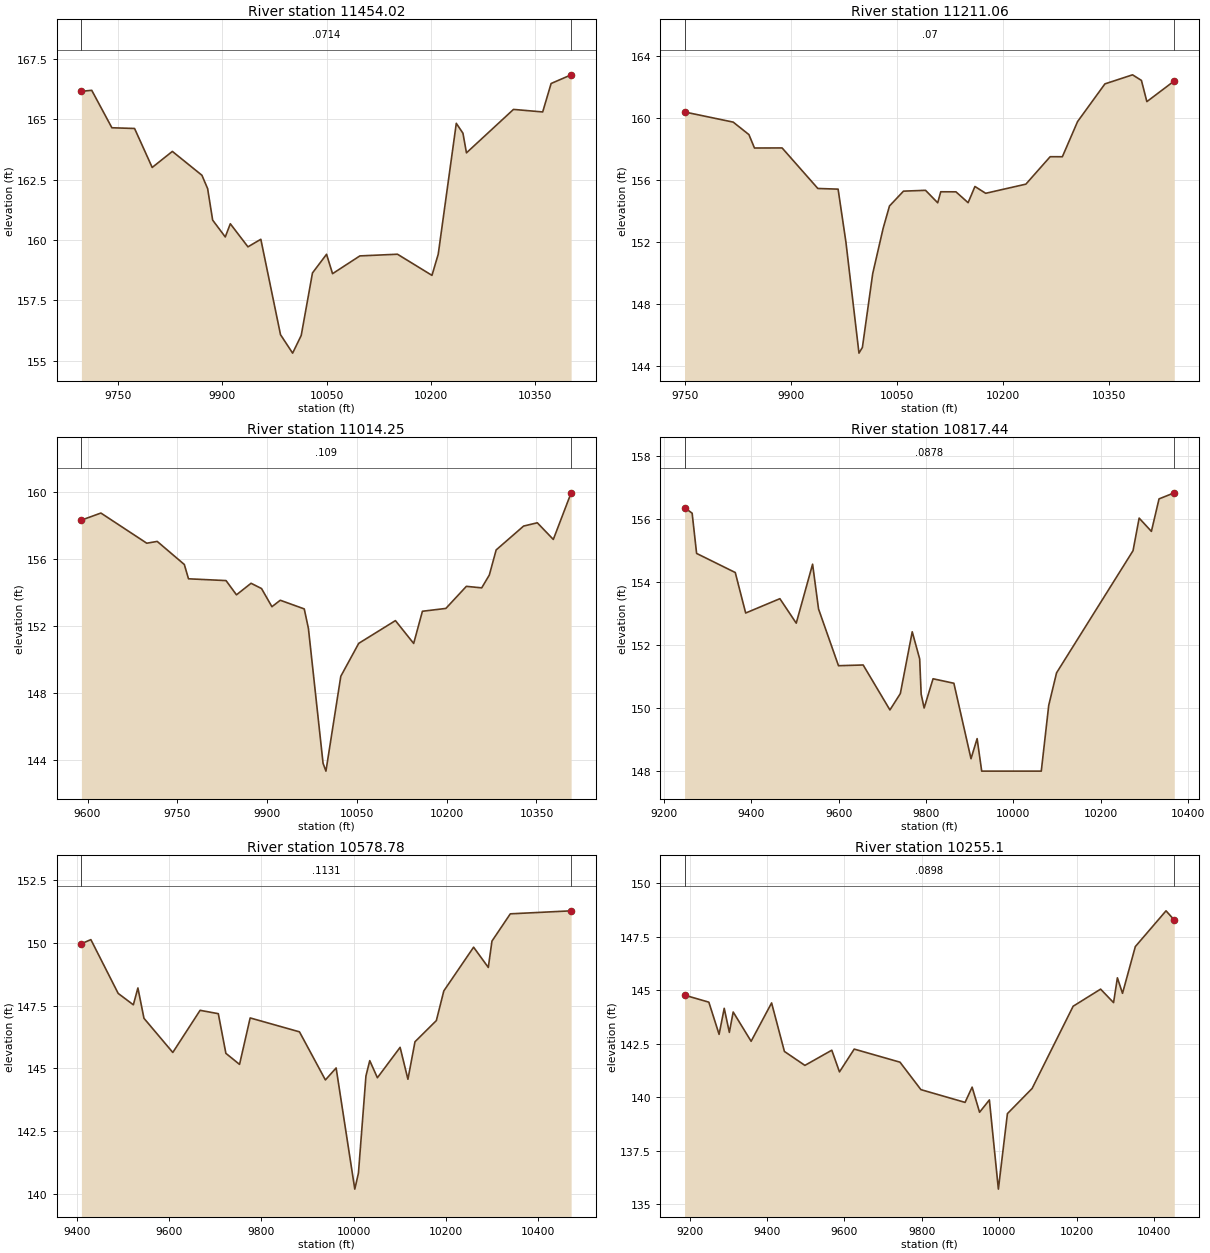
Type RM Length L Ch R = 1 ,11454.02,242.965800,242.965800,242.965800
XS GIS Cut Line= 6
1217696.89564359620373.7412594411217587.22306526620140.340422198
1217571.68327099620119.371218279 1217555.3277427620100.645750478
1217515.11280233620044.6820632671217277.38758472619820.390153185
#Sta/Elev= 30
 9697.12166.15989711.988166.20199740.988164.64999773.613164.62049798.988163.0056
9827.988163.67079870.515162.68229878.738162.12749885.944160.82529904.112160.1265
9911.362160.67289936.737159.71729955.269160.03049983.584156.077810001.01155.3135
10013.39156.047410029.57158.634910049.81159.408210058.46158.605210097.75159.3411
10151.87159.410810201.49158.535110210.51159.413610236.49164.833510246.06164.4236
10251.11163.610810318.77165.410510360.79165.305410372.89166.483710401.72166.8432
#Mann= 3 , 0 , 0
 9697.12  0.0714       0 9697.12  0.0714       010401.72  0.0714       0
#XS Ineff= 2 , 0
       0                               0
Bank Sta=9697.12,10401.72
Exp/Cntr=0.3,0.1

Type RM Length L Ch R = 1 ,11211.06,196.808800,196.808800,196.808800
XS GIS Cut Line= 6
1217907.26932865620221.3278917671217866.66532451620165.700420842
1217824.07072437620100.0621761981217773.95144212620007.981891632
1217730.85581976619944.2449134291217453.18143791619708.521337479
#Sta/Elev= 30
9749.027160.39999817.897159.74519840.154158.93959847.976158.07639887.087 158.081
9937.686155.46759966.347155.42499977.426152.01149995.893144.854710000.74145.2232
10015.33 149.97810030.07152.893810039.09154.339510058.89 155.29610090.11 155.349
10107.32154.544210111.63155.255310133.14155.251910150.36154.551510160.02 155.596
10175.23155.157210232.13155.746610266.48157.515110283.77157.513610305.29159.7804
10344.02162.210710383.08162.793510395.66 162.43410403.36161.066210442.18162.4006
#Mann= 3 , 0 , 0
9749.027    0.07       09749.027    0.07       010442.18    0.07       0
#XS Ineff= 2 , 0
       0                               0
Bank Sta=9749.027,10442.18
Exp/Cntr=0.3,0.1

Type RM Length L Ch R = 1 ,11014.25,196.808800,196.808800,196.808800
XS GIS Cut Line= 6
1218090.43415597620249.8864991961217974.29770589619925.120873094
1217939.44125593619895.916466534 1217898.6892122619864.685211688
1217795.12130654619772.246975183 1217591.0198001619650.589272201
#Sta/Elev= 30
9589.716158.32969622.297158.75119698.951156.95069716.373157.05889761.669155.6797
9768.637 154.8269831.355154.71929848.776153.87029873.166154.55879890.588154.2471
9908.009153.16079921.946153.54569962.014153.02919968.987151.86059993.443143.8143
9998.242 143.34510023.07149.006310053.03150.972810114.34  152.3310144.82150.9667
10159.41 152.888 10198.6153.057610232.85 154.37610258.49154.285710271.17155.0493
10282.63156.549810328.46157.974310351.38  158.1710378.11157.175910407.89159.9587
#Mann= 3 , 0 , 0
9589.716   0.109       09589.716   0.109       010407.89   0.109       0
#XS Ineff= 2 , 0
       09928.326                       0
Bank Sta=9589.716,10407.89
Exp/Cntr=0.3,0.1

Type RM Length L Ch R = 1 ,10817.44,238.655300,238.655300,238.655300
XS GIS Cut Line= 4
1218294.19521314620373.7412594411218123.16334221 619753.25271067
1217884.73412862619665.5015231221217675.74774775619587.564613119
#Sta/Elev= 30
9247.432156.35219264.794156.17389275.004154.89869363.487154.29359387.309153.0103
9465.582153.46439503.017152.68899540.452154.55759554.065153.13779599.722151.3401
9656.161151.36369717.418149.9387 9741.24150.45749768.466152.41519785.482151.5568
9788.885150.43849795.691150.0007 9816.11150.92679863.755150.78449902.958148.3935
9916.942149.0297 9927.43     14810063.77     14810080.82150.083210098.73151.1145
10273.74154.984710287.74156.017910315.75155.597310333.26156.627110368.17156.8189
#Mann= 3 , 0 , 0
9247.432  0.0878       09247.432  0.0878       010368.17  0.0878       0
#XS Ineff= 2 , 0
       09870.686                       0
Bank Sta=9247.432,10368.17
Exp/Cntr=0.3,0.1

Type RM Length L Ch R = 1 ,10578.78,323.683100,323.683100,323.683100
XS GIS Cut Line= 6
1218362.11556548620046.1254420131218330.15304679619648.591614783
1218159.44907185619529.1658989491218047.20247424619442.788432345
1217977.33434233619391.9247462151217788.74109492619264.976011276
#Sta/Elev= 30
9409.585149.96679430.137150.12859489.383147.98359522.297147.52879532.172148.2003
9545.337146.99049607.874145.6285 9667.12147.30879706.617147.17519723.074145.5927
9752.697145.15239775.737 147.0059882.714146.4507 9938.97144.53229962.254145.0099
10002.74140.177510010.66140.815810026.94144.690310035.22145.301810051.78144.6196
10101.07145.832110118.02  144.5610133.35146.054810179.69146.899710195.92148.0839
10260.54149.826610292.39149.019710300.35150.069510340.16151.156910472.15151.2771
#Mann= 3 , 0 , 0
9409.585  0.1131       09409.585  0.1131       010472.15  0.1131       0
#XS Ineff= 2 , 0
       09848.311        10134.03       0
Bank Sta=9409.585,10472.15
Exp/Cntr=0.3,0.1

Type RM Length L Ch R = 1 , 10255.1,374.892300,374.892300,374.892300
XS GIS Cut Line= 6
1218555.88833559619986.1957193321218605.82977113619586.664234653
1218547.89770585619420.8586685361218265.90685716 619212.06231688
1218104.41775793619173.1491480471217936.61453435619193.125722289
#Sta/Elev= 30
9187.216144.76649249.962144.43749276.413142.93359289.639144.15099302.864143.0263
9312.783143.97799359.073142.60929411.974144.40249445.038142.1344 9497.94141.4825
9567.374 142.1929587.212141.17819625.305142.24399743.466141.63229797.499140.3487
9911.487139.7527 9929.71140.46689948.903139.29169974.237139.86829997.464135.6981
10020.82139.226810084.59140.403810190.51144.247510261.38145.046510294.87144.4168
10304.78145.5761   10318144.850410351.04147.035510430.33148.707510451.67148.2765
#Mann= 3 , 0 , 0
9187.216  0.0898       09187.216  0.0898       010451.67  0.0898       0
#XS Ineff= 2 , 0
       09795.704        10155.21       0
Bank Sta=9187.216,10451.67
Exp/Cntr=0.3,0.1

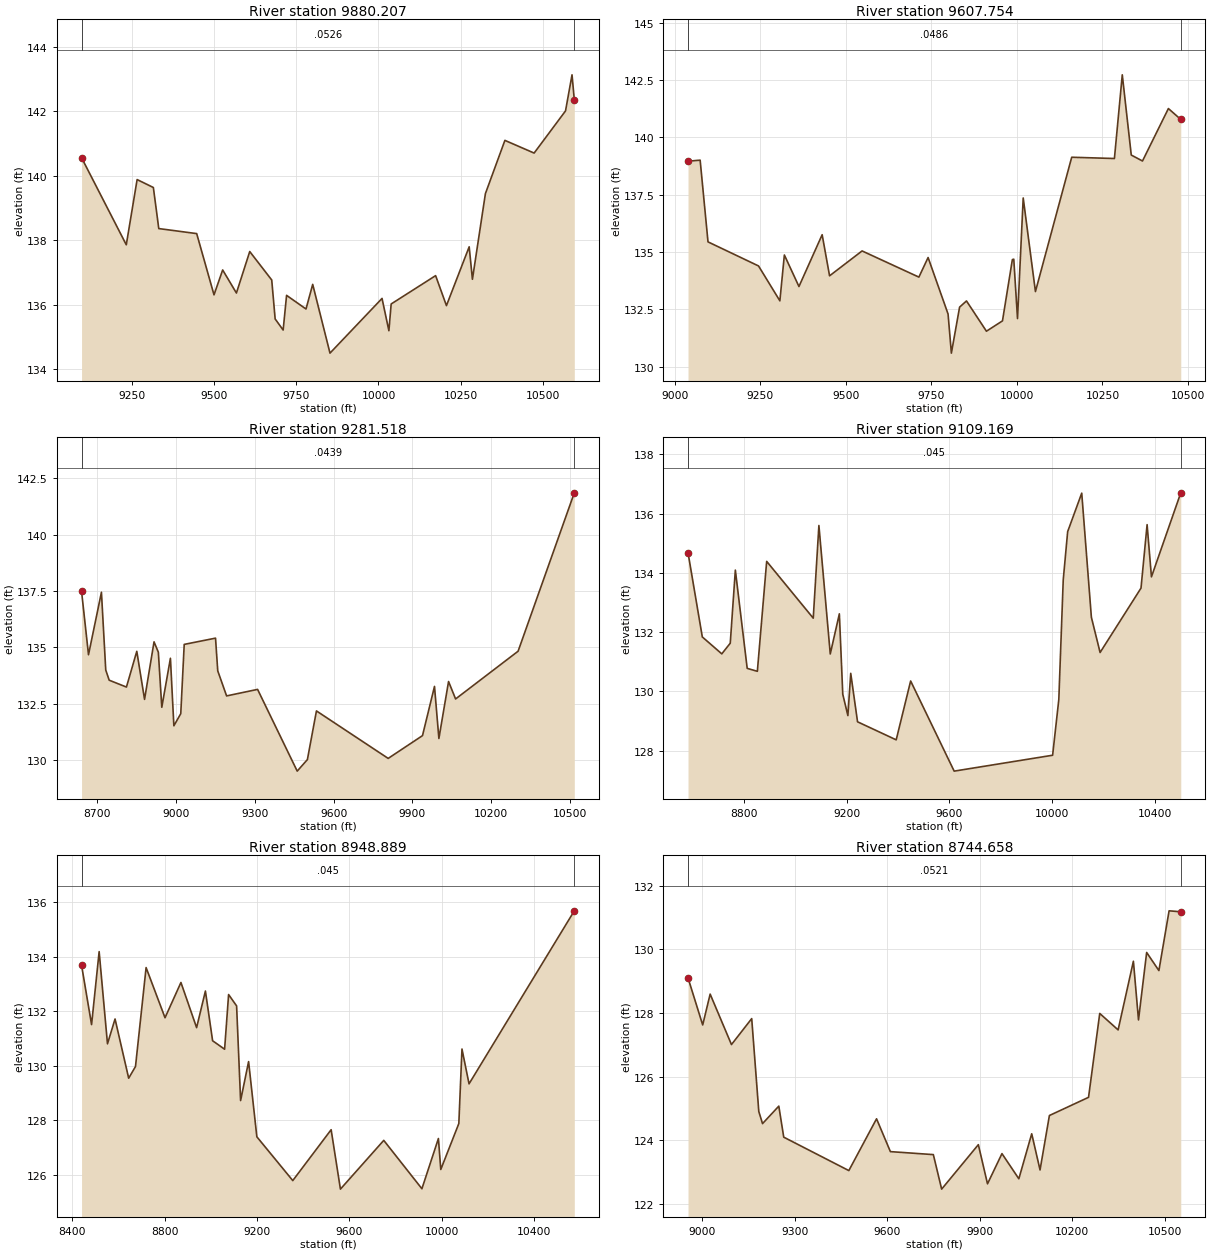
Type RM Length L Ch R = 1 ,9880.207,272.453100,272.453100,272.453100
XS GIS Cut Line= 5
1218755.65407789 619836.371412561218805.59551349619279.024991468
1218735.87595293 619079.181311161218447.77941826618980.405356377
1218026.33534467618944.187506303
#Sta/Elev= 30
9096.853 140.557 9232.93137.8558 9265.87139.8779 9315.28139.63219331.749138.3585
9447.039138.20289499.742136.30359526.094137.07539567.884136.35989608.444137.6464
9675.305136.76419685.729135.55599710.053135.21269720.477136.28789779.548135.8651
9799.944136.62799852.518134.496610010.84136.192910031.65135.190710038.58136.0205
10173.79136.899210206.72135.969710275.87137.793310285.75136.786510325.26139.4438
10384.53141.093310473.44140.699910568.94142.0075 10588.7143.125910595.64142.3481
#Mann= 3 , 0 , 0
9096.853  0.0526       09096.853  0.0526       010595.64  0.0526       0
#XS Ineff= 2 , 0
       09905.701        10125.96       0
Bank Sta=9096.853,10595.64
Exp/Cntr=0.3,0.1

Type RM Length L Ch R = 1 ,9607.754,326.236100,326.236100,326.236100
XS GIS Cut Line= 6
1218919.46198663619496.7696506231218924.58872038619116.848591015
1218545.65395799618763.3875131911218453.01097018618829.085697457
 1218389.2248787618852.1485251041218030.02019438618850.226051912
#Sta/Elev= 30
9038.893138.9598 9074.33139.00539097.298135.44499244.949134.39619307.291132.8764
9320.415134.8736 9363.07133.49979430.864135.75719452.518133.96569547.514135.0503
9713.517133.90959740.436134.76289798.762132.30259808.451130.5973  9832.5132.6023
  9852.6 132.8719910.925131.55219957.777 132.0039986.695134.67349990.802134.6907
10001.71132.104710018.35137.358410054.08133.2798 10160.1 139.13310284.87139.0776
10307.85142.724310334.11139.228610366.93138.9695 10442.6141.254810478.78140.7806
#Mann= 3 , 0 , 0
9038.893  0.0486       09038.893  0.0486       010478.78  0.0486       0
#XS Ineff= 2 , 0
       09769.686        10037.96       0
Bank Sta=9038.893,10478.78
Exp/Cntr=0.3,0.1

Type RM Length L Ch R = 1 ,9281.518,172.349100,172.349100,172.349100
XS GIS Cut Line= 5
1219023.34017262 619556.699373321219009.98007905 619062.50397931
 1218376.0991675618551.8776893911218164.80847847618509.619551614
1217820.75040379 618436.01355885
#Sta/Elev= 30
8640.485137.48418666.961134.67778716.191137.44428732.601133.9998 8745.73133.5505
 8811.37133.24688850.755134.83048880.293 132.7028916.395135.24918932.805134.7892
8945.933132.35238978.754134.52128991.882131.53269018.138132.06829031.266135.1362
9150.471135.41239158.897133.96619192.601132.85499310.563133.1437 9461.39 129.525
9500.144130.03629534.608132.19049807.688130.08829938.289 131.0979983.954133.2749
10000.68130.969810037.49133.491510064.25132.720110302.19134.833710516.15141.8464
#Mann= 3 , 0 , 0
8640.485  0.0439       08640.485  0.0439       010516.15  0.0439       0
#XS Ineff= 2 , 0
       09929.754        10081.56       0
Bank Sta=8640.485,10516.15
Exp/Cntr=0.3,0.1

Type RM Length L Ch R = 1 ,9109.169,160.280400,160.280400,160.280400
XS GIS Cut Line= 6
1219109.23944187619470.8001040971219059.29800621618971.385748282
1218417.61403406618390.2861112211218295.02328172618351.578681916
1218217.26650369618329.098204285 1217886.6261217618243.551433489
#Sta/Elev= 30
8582.361134.68048638.032131.83458713.868131.2635 8746.84131.62378766.623134.0914
8812.784130.7737 8852.35130.67468888.619134.38559069.965132.46819091.956135.5968
9136.218131.26049171.627 132.6159184.906129.90089204.809129.17959215.889130.6067
9242.446128.96959392.937128.36079449.192130.34759618.672127.304710002.01 127.841
10026.12129.723410043.34133.760210060.56135.389910115.36136.688910152.93132.4983
10186.87131.309610346.14133.482910369.86135.625710386.81133.863110500.99136.6998
#Mann= 3 , 0 , 0
8582.361   0.045       08582.361   0.045       010500.99   0.045       0
#XS Ineff= 2 , 0
       09743.465        10033.64       0
Bank Sta=8582.361,10500.99
Exp/Cntr=0.3,0.1

Type RM Length L Ch R = 1 ,8948.889,204.230200,204.230200,204.230200
XS GIS Cut Line= 6
1219159.18087739619458.8141595721219142.23565912619002.994540393
1219062.12475288618768.8857359441218495.95861289618244.238446206
1218192.31468451618160.3368344461217846.71995032618154.343862161
#Sta/Elev= 30
 8439.58133.6826 8483.02131.50148515.851134.17898551.965130.79658584.796131.7081
8643.892129.5352 8673.44 129.9648719.403133.59368801.481131.75318870.426133.0468
8938.357131.39078976.501132.73299007.709130.90979059.723130.59899077.061132.6043
9111.737132.18749129.075128.71469163.722130.14469199.506 127.3869355.248125.7797
9521.555 127.6469561.811125.46619749.673127.25449915.031125.48039986.617127.3231
9996.828126.186710075.12127.872210088.73130.605510119.36129.3284 10575.7135.6758
#Mann= 3 , 0 , 0
 8439.58   0.045       0 8439.58   0.045       0 10575.7   0.045       0
#XS Ineff= 2 , 0
       09784.026                       0
Bank Sta=8439.58,10575.7
Exp/Cntr=0.3,0.1

Type RM Length L Ch R = 1 ,8744.658,218.447600,218.447600,218.447600
XS GIS Cut Line= 6
1219171.16682196 618771.620005981219103.53458437618567.413947955
1218580.34679806618077.8292385191218438.02654761618008.514870256
1218296.19287053617974.5546940571217936.61453435618020.500814795
#Sta/Elev= 30
8953.365129.1049 9000.97127.62339025.162128.59439094.284 127.007 9159.95127.8235
9182.951124.90139195.042124.52169247.861125.0712 9263.83124.09549475.014123.0444
9564.879124.67299609.812123.64069749.103123.54679776.044122.46139895.058123.8592
9924.771122.62779971.692123.577810026.43 122.78710068.19 124.20210095.18123.0648
10125.54124.775710252.47 125.34810288.85127.985710348.39127.4683   10398129.6273
10414.54127.7821   10441129.903310480.69129.333610513.76131.212810551.66131.1829
#Mann= 3 , 0 , 0
8953.365  0.0521       08953.365  0.0521       010551.66  0.0521       0
#XS Ineff= 2 , 0
       0  9736.4        10134.79       0
Bank Sta=8953.365,10551.66
Exp/Cntr=0.3,0.1