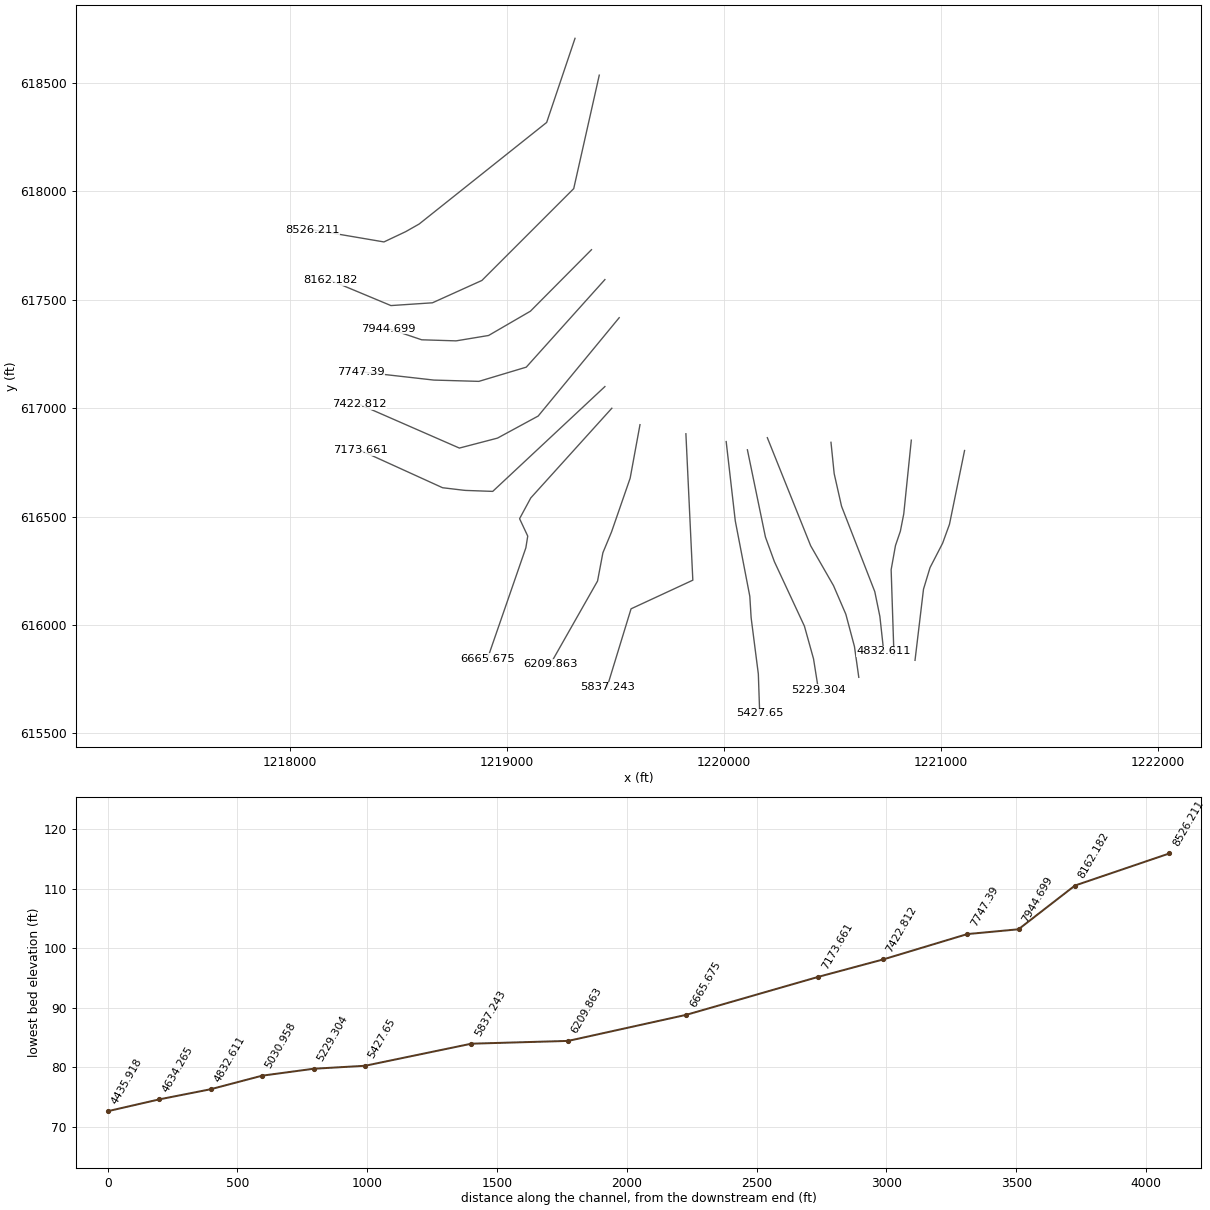
HEC-RAS study 241_ras.prj: 241

--- 241_ras.g01 (geometry) --- (continued)

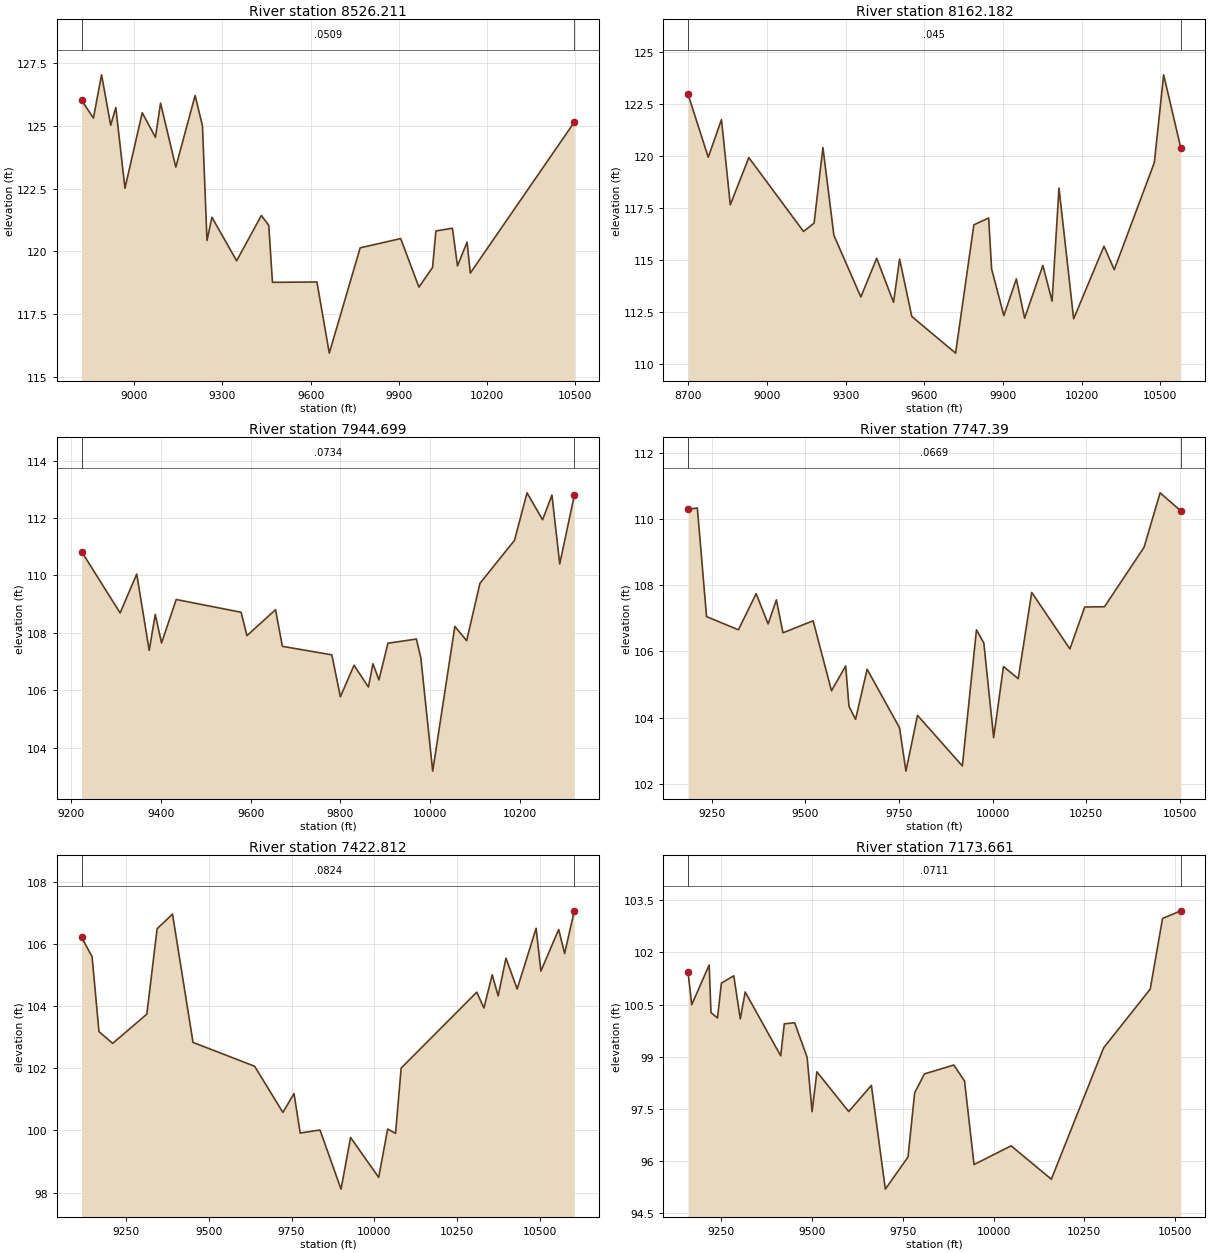
Type RM Length L Ch R = 1 ,8526.211,364.028400,364.028400,364.028400
XS GIS Cut Line= 6
1219313.00049898618705.6973109991219182.23579657618317.789969712
1218594.13722584617849.2906286571218532.01573947617814.064605698
1218431.78626454617766.6872929191218102.42010048617822.732729897
#Sta/Elev= 30
8820.222126.02918860.663125.31748888.361127.04218919.521 125.0278936.833125.7376
8967.993122.51499026.851125.5293 9071.86124.54739089.171125.91259141.104123.3588
9206.887126.21779231.918124.99949247.279120.42959264.103121.35559348.222119.6193
 9432.34121.42689457.576121.03669470.193118.75959621.607118.77359663.666115.9338
9768.814120.13669906.734 120.5069968.858118.569810015.27119.352110026.59120.8088
10082.93120.919710100.16 119.41410132.82120.365710143.71119.128210497.87125.1529
#Mann= 3 , 0 , 0
8820.222  0.0509       08820.222  0.0509       010497.87  0.0509       0
#XS Ineff= 2 , 0
       09800.999        10146.38       0
Bank Sta=8820.222,10497.87
Exp/Cntr=0.3,0.1

Type RM Length L Ch R = 1 ,8162.182,217.483500,217.483500,217.483500
XS GIS Cut Line= 6
1219424.86931467618535.896430016 1219307.0075267618012.510185122
1218883.50415298617589.0068113651218655.47025847 617485.93934986
1218463.99609408617473.1426808241218186.32171229617589.006811365
#Sta/Elev= 30
8698.957122.98448776.055119.9516  8826.5121.76418860.129117.66548930.752119.9371
9139.258 116.3869179.614116.78569213.244  120.42 9255.12116.19959357.926 113.234
9418.244115.0965 9482.47112.98049505.669115.05839552.067112.2987  9719.1110.5357
9788.697116.70469845.047117.03149856.446114.58179903.062112.33889950.728 114.102
9982.222112.213510051.78114.750610086.92113.036610113.23118.470710169.13112.1851
10284.82115.676410323.93114.548110476.79119.697310512.34123.915410577.56120.4079
#Mann= 3 , 0 , 0
8698.957   0.045       08698.957   0.045       010577.56   0.045       0
#XS Ineff= 2 , 0
       09824.306        10111.11       0
Bank Sta=8698.957,10577.56
Exp/Cntr=0.3,0.1

Type RM Length L Ch R = 1 ,7944.699,197.309300,197.309300,197.309300
XS GIS Cut Line= 6
1219388.91148108617730.8404884341219107.24178439617447.173134327
1218914.34958703 617335.194439341218764.39593681617310.382912355
1218605.82977113 617315.327744381218452.01014957617367.266837403
#Sta/Elev= 30
9224.129110.83499309.866108.69569346.854110.04989374.595107.39299388.047108.6431
9402.016107.6492 9434.61109.16349578.955108.71929591.899 107.9059655.564108.8085
9670.738107.53319780.753107.23659799.721 105.776 9830.07106.8726 9862.14106.1169
9872.157106.92739885.512106.36459905.546107.64129968.781107.7868 9978.69107.1297
10005.08103.187310054.32108.226210080.58107.730410110.12109.724610187.15111.2287
10214.86112.878210249.49111.940310270.26112.798610287.58110.4014   10320112.7913
#Mann= 3 , 0 , 0
9224.129  0.0734       09224.129  0.0734       0   10320  0.0734       0
#XS Ineff= 2 , 0
       09682.653        10115.99       0
Bank Sta=9224.129,10320
Exp/Cntr=0.3,0.1

Type RM Length L Ch R = 1 , 7747.39,324.577500,324.577500,324.577500
XS GIS Cut Line= 5
 1219450.8388612617593.0021262321219088.16323963617189.145438343
1218869.52055103617123.5526317361218661.76417902 617129.54560402
1218326.15773189617167.501095057
#Sta/Elev= 30
9186.183110.29839211.124110.33629235.675107.05299320.811106.65479368.253107.7486
9400.183 106.8319422.266107.5589 9439.87106.56389520.472 106.9279569.575104.8104
9607.434 105.5629616.253 104.3419633.892103.94799664.759105.46149751.371103.6922
9768.497102.38159799.325104.0675 9919.21102.53799956.888 106.6539976.597106.2535
10002.85103.395910029.11105.5434 10068.5105.1758 10104.6107.7829 10206.6106.0763
10246.22 107.34310299.05107.3516 10404.7109.147710447.62 110.79510502.84110.2506
#Mann= 3 , 0 , 0
9186.183  0.0669       09186.183  0.0669       010502.84  0.0669       0
#XS Ineff= 2 , 0
       09790.853        10098.02       0
Bank Sta=9186.183,10502.84
Exp/Cntr=0.3,0.1

Type RM Length L Ch R = 1 ,7422.812,249.151600,249.151600,249.151600
XS GIS Cut Line= 5
1219516.76155615617417.2082729641219143.19961804616963.740037873
1218955.41982022616861.8595092891218779.62596697 616815.91338855
1218318.16710222617017.676788315
#Sta/Elev= 30
9116.618106.21239148.469105.58679169.108103.18219210.388102.80089313.587103.7422
9344.547 106.4879390.986106.95979452.906102.83269638.664102.06679723.963100.5821
9757.556101.18819776.21999.917919835.941100.01649899.39698.114699928.20699.77599
10012.9898.4921310040.11100.047710063.8599.90707 10080.8 102.00810308.92104.4483
10330.41103.938310355.47105.006910373.38104.326810396.97 105.54210430.67104.5502
10487.96106.501910502.28105.125410555.99106.4625 10573.9105.690210603.12107.0638
#Mann= 3 , 0 , 0
9116.618  0.0824       09116.618  0.0824       010603.12  0.0824       0
#XS Ineff= 2 , 0
       09864.411                       0
Bank Sta=9116.618,10603.12
Exp/Cntr=0.3,0.1

Type RM Length L Ch R = 1 ,7173.661,507.985300,507.985300,507.985300
XS GIS Cut Line= 6
 1219450.8388612617099.5807426571218933.44558859616616.147646248
 1218809.4205752616620.5760273641218798.64516938616621.497635841
1218702.15744057616633.0181674211218322.16241705616805.925101474
#Sta/Elev= 30
9157.981 101.4349168.243100.49399216.299101.63669221.199100.26729239.159100.1152
9249.937101.1137 9284.06101.32599302.021100.08629315.491100.86029413.32699.02645
9423.25499.94493 9451.7799.975569486.11598.984239499.82597.421079513.05698.56671
9600.74197.424919663.21398.176959701.65795.196199764.12996.118849782.46397.96324
9809.40398.506579890.29998.761849919.84698.303129946.10995.9022410048.2296.43986
10159.0295.48041 10303.299.2571610431.46100.9415 10465.4 102.97210515.66103.1912
#Mann= 3 , 0 , 0
9157.981  0.0711       09157.981  0.0711       010515.66  0.0711       0
#XS Ineff= 2 , 0
       09633.869        10101.54       0
Bank Sta=9157.981,10515.66
Exp/Cntr=0.3,0.1

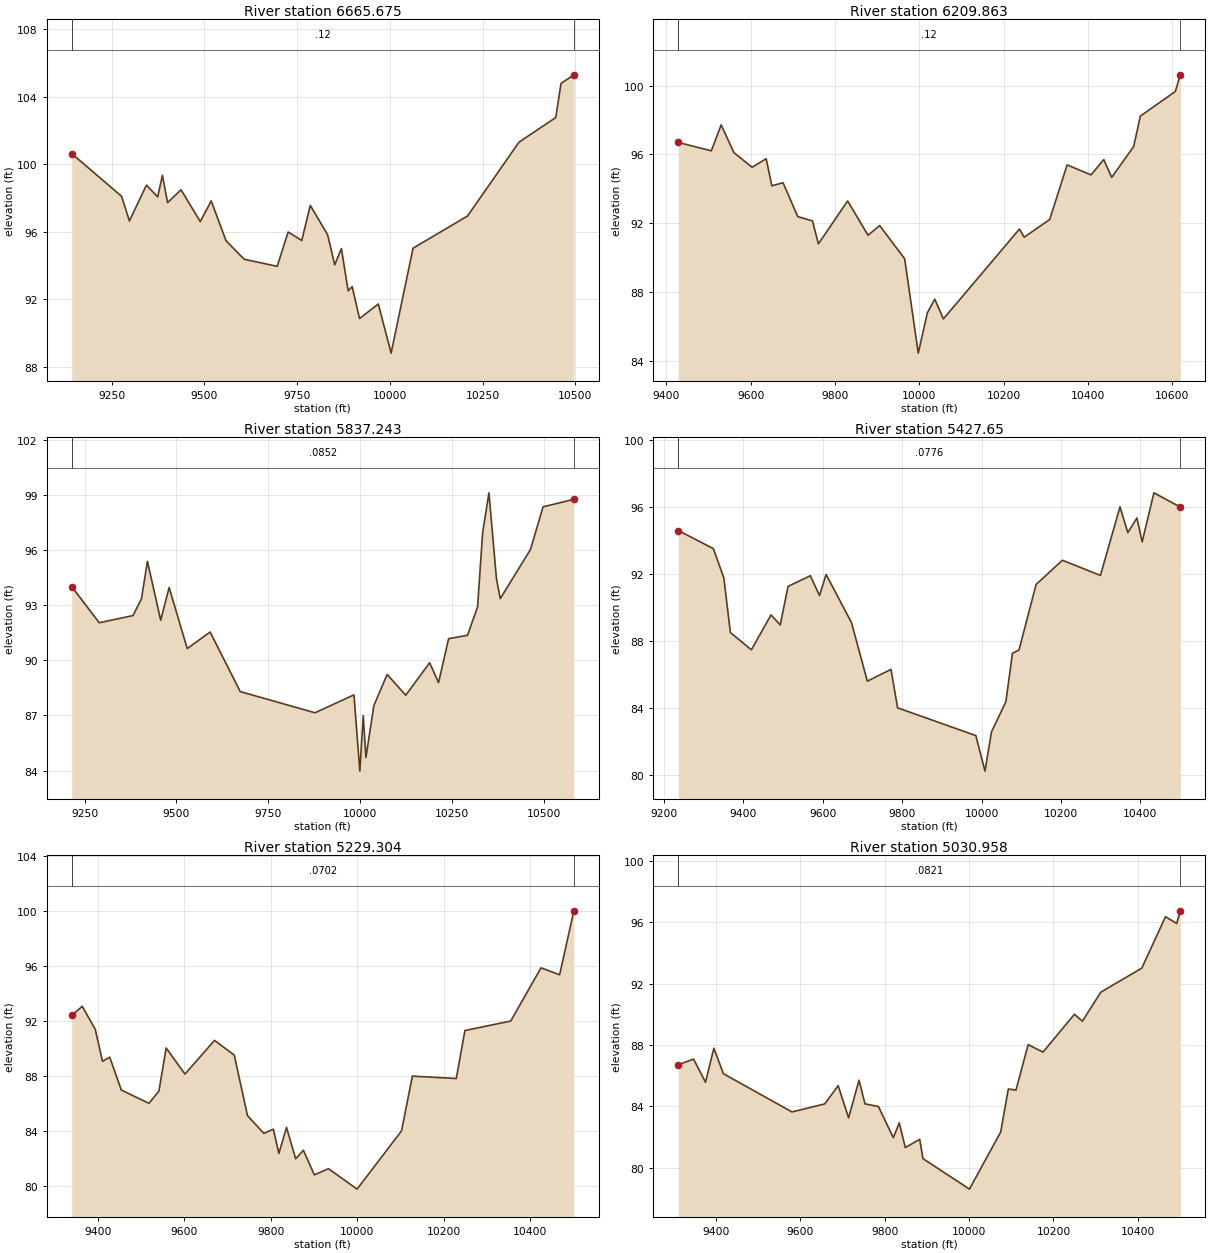
Type RM Length L Ch R = 1 ,6665.675,455.812600,455.812600,455.812600
XS GIS Cut Line= 6
1219482.80137995616999.697871491  1219108.982779 616585.99577938
1219057.30034882616490.2952285561219094.93931851616409.957400262
1219086.23162562616355.7108223591218908.93586317615843.522846505
#Sta/Elev= 30
9142.431100.62299276.68798.101889297.86996.643489343.75698.760029374.12398.06485
9386.83299.343949400.80197.725819437.102 98.48669488.96196.603019518.45997.82654
9558.48595.467929607.40594.375799696.35293.958469725.91695.988129762.64895.48573
9785.57597.562349832.296 95.83079851.48494.043879869.59995.007529887.71592.50658
9898.58492.758049918.41690.871349969.02391.72973 10003.688.8255410062.6795.02879
10209.6696.9351210348.32101.297910447.47102.756410461.71104.7714 10496.3105.2837
#Mann= 3 , 0 , 0
9142.431    0.12       09142.431    0.12       0 10496.3    0.12       0
#XS Ineff= 2 , 0
       09557.683                       0
Bank Sta=9142.431,10496.3
Exp/Cntr=0.3,0.1

Type RM Length L Ch R = 1 ,6209.863,372.620200,372.620200,372.620200
XS GIS Cut Line= 6
1219612.64911246616923.7868894341219567.30161223616677.013837427
1219481.40866864616429.1474540081219441.56610346616333.012700856
  1219416.878685616202.6325596121219199.13402587 615819.08233434
#Sta/Elev= 30
 9428.1596.690819506.71896.204179530.06997.713619560.09196.103099603.45695.24503
9636.813 95.74499650.15694.168799676.84394.347869711.721 92.37539746.70892.12565
9760.70390.790949830.072 93.28689878.46491.291439906.11791.856139965.35289.92481
9997.62884.4353710019.2486.7740310036.8287.5740710057.2886.4248710237.7391.65279
10249.0591.1793510309.4392.2078410350.9195.38602 10407.594.8025210437.6895.69217
10456.5594.65908 10508.896.4535210524.46 98.220610607.45 99.653610619.38 100.624
#Mann= 3 , 0 , 0
 9428.15    0.12       0 9428.15    0.12       010619.38    0.12       0
#XS Ineff= 2 , 0
       09855.696                       0
Bank Sta=9428.15,10619.38
Exp/Cntr=0.3,0.1

Type RM Length L Ch R = 1 ,5837.243,409.592000,409.592000,409.592000
XS GIS Cut Line= 4
1219824.40079936616881.8360835311219856.36331812616206.627874449
1219571.44992879616074.5315771851219460.82714832615713.206490904
#Sta/Elev= 30
9214.71794.003999289.49592.038689381.46192.428049404.45393.328699420.87595.37742
9457.00592.176829479.996 93.95549529.26490.63431 9591.6791.532269673.782 88.2934
9877.42287.141939983.561  88.1169999.59183.9681610008.8786.9866810016.1184.70864
10037.8187.5357510073.9789.22666 10124.688.0951510189.6989.8620910213.9988.78309
10241.4491.1712910292.9191.3569710320.3692.9017110334.0896.9244510351.2499.10528
10371.82 94.429710382.1293.3495310464.4796.0237710498.7898.3431410582.6198.75219
#Mann= 3 , 0 , 0
9214.717  0.0852       09214.717  0.0852       010582.61  0.0852       0
#XS Ineff= 2 , 0
       09792.668        10153.46       0
Bank Sta=9214.717,10582.61
Exp/Cntr=0.3,0.1

Type RM Length L Ch R = 1 , 5427.65,198.346400,198.346400,198.346400
XS GIS Cut Line= 6
1220010.18293974616845.8782499131220052.13374561616480.306941465
1220119.17809942616132.1991318461220125.32380003616032.799699083
1220158.49383932615773.9412525741220164.79850072615592.302468985
#Sta/Elev= 30
9235.80194.613659324.32793.531529350.74691.783369367.25888.527129420.096 87.4951
9469.63189.577659492.74888.979829512.56291.280369568.70291.916019591.81990.73044
 9608.4191.991459672.24489.12733 9712.3485.623579771.92486.32957 9788.5584.03452
9985.75282.3783610008.7680.25877 10025.282.6006110061.3884.3929210077.9587.28446
10094.5287.48828 10137.691.3951510203.8892.8381410299.63 91.931310348.9996.02472
10368.7194.4856510391.7195.3601310404.8693.93347 10434.496.8614810500.9596.01296
#Mann= 3 , 0 , 0
9235.801  0.0776       09235.801  0.0776       010500.95  0.0776       0
#XS Ineff= 2 , 0
       0                               0
Bank Sta=9235.801,10500.95
Exp/Cntr=0.3,0.1

Type RM Length L Ch R = 1 ,5229.304,198.346500,198.346500,198.346500
XS GIS Cut Line= 6
1220108.06815344616807.9227588921220191.22150676616405.622839967
1220232.43551184 616292.294932681220371.09978618615994.536562366
1220413.08420288615843.7516358441220435.60255816615701.780387087
#Sta/Elev= 30
9340.28792.418679364.49793.078679394.60191.404469411.32689.07036 9428.0589.37449
 9454.8186.976999518.75686.009789541.77786.907139558.50290.042829601.98688.14149
9670.33390.596779715.94989.524049746.48385.114329784.39383.816849806.26784.12308
9819.07682.359329836.74684.252549857.95181.965759875.71582.588929901.06380.79791
9933.74581.246239999.83979.7576310102.5984.0004510127.6687.9911710229.1487.81833
10249.1491.3154410354.97 92.004310425.0795.8822810468.1195.3783610500.93100.0376
#Mann= 3 , 0 , 0
9340.287  0.0702       09340.287  0.0702       010500.93  0.0702       0
#XS Ineff= 2 , 0
       0                               0
Bank Sta=9340.287,10500.93
Exp/Cntr=0.3,0.1

Type RM Length L Ch R = 1 ,5030.958,198.346500,198.346500,198.346500
XS GIS Cut Line= 6
1220199.96039492616863.8571667081220399.82366833616365.340285999
1220505.34824731616181.2065704211220562.05544144616049.611575216
1220601.85907767615900.3121319851220621.80279103615758.570973038
#Sta/Elev= 30
9310.40686.703719346.76787.072349375.04485.563999394.93987.784539417.46186.12151
9580.05683.628049657.81984.149739689.63185.344689714.37483.241089739.11785.69582
9753.25584.153349785.06883.980589820.41481.946899834.55382.915479848.78481.30443
9883.03381.841869890.67980.5846510000.9478.5930910075.02 82.318110093.1385.12585
10111.2485.0499410140.1888.0173410175.3687.5295410249.7589.9940410268.7789.54605
10312.5991.4425610409.6293.00529 10465.996.3630810492.32 95.917610500.9396.74401
#Mann= 3 , 0 , 0
9310.406  0.0821       09310.406  0.0821       010500.93  0.0821       0
#XS Ineff= 2 , 0
       09760.327                       0
Bank Sta=9310.406,10500.93
Exp/Cntr=0.3,0.1

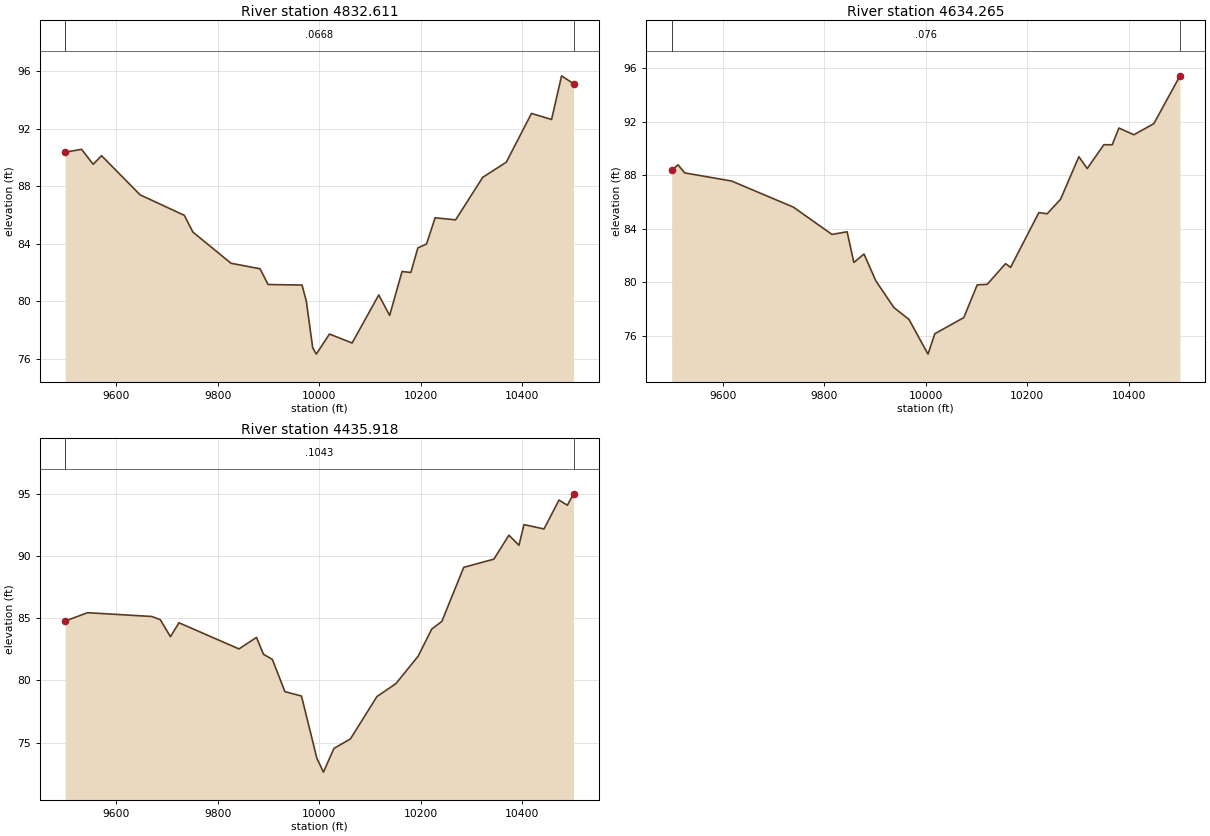
Type RM Length L Ch R = 1 ,4832.611,198.346500,198.346500,198.346500
XS GIS Cut Line= 6
1220493.56361269616842.4873883281220508.29967345 616697.94458127
1220542.30515001616547.3920482651220695.61405398616153.616068953
1220719.08242615616039.1997003921220736.70409899615878.166955782
#Sta/Elev= 30
9499.06590.355149531.21490.55705 9554.2489.517549570.69290.115869646.81287.38992
9733.763 85.96919750.73684.803569825.91382.633219883.04482.250379898.95881.15542
 9965.7781.119799974.207  80.0129986.869 76.75759993.902 76.3154 10019.977.71237
10064.5377.0890410117.0480.4293610138.5179.0111310162.9382.0610510180.3281.99495
10194.08 83.701810211.15 83.972710228.1385.7944310268.5285.6529910322.0188.61066
10368.4389.6628410418.0493.0520810457.6292.6319410477.3795.6678810500.9295.11621
#Mann= 3 , 0 , 0
9499.065  0.0668       09499.065  0.0668       010500.92  0.0668       0
#XS Ineff= 2 , 0
       09841.536                       0
Bank Sta=9499.065,10500.92
Exp/Cntr=0.3,0.1

Type RM Length L Ch R = 1 ,4634.265,198.346400,198.346400,198.346400
XS GIS Cut Line= 6
1220864.01672732616852.4899413941220829.22087765616512.396770757
1220813.58348016616432.6420812431220790.99929809616366.292879455
1220771.01295384 616254.871406261220784.09529206615859.982034349
#Sta/Elev= 30
9499.08888.37508 9511.6888.771329524.85988.169789617.10887.56246 9739.0885.60604
9815.08583.564319844.85483.765269858.16881.465229878.13982.100119901.61480.08268
9936.99978.097369966.83177.2046610004.26 74.608210017.7776.1363610074.8577.34247
 10101.379.7912110121.0379.8309810157.1481.3794710166.9881.0972510222.8185.19918
10239.23 85.113410265.5186.1951310301.6589.3824310318.0888.4961910350.9390.28214
10367.3590.2718310380.4991.5269410410.0491.0239110449.4391.8574510500.9595.43451
#Mann= 3 , 0 , 0
9499.088   0.076       09499.088   0.076       010500.95   0.076       0
#XS Ineff= 2 , 0
       0                               0
Bank Sta=9499.088,10500.95
Exp/Cntr=0.3,0.1

Type RM Length L Ch R = 1 ,4435.918,198.346500,198.346500,198.346500
XS GIS Cut Line= 6
1221109.64051076 616804.64617936 1221040.0503551616464.268654125
1221008.34668244616376.8862374481220950.38757403616264.527089389
1220920.25181505616165.0653940321220881.15542276615837.034199734
#Sta/Elev= 30
9499.04484.759199543.09385.425699669.715 85.12219686.41384.86636 9706.45 83.4993
 9723.2484.617639841.55982.517289876.00983.441169889.82382.086779907.38581.67262
9932.11579.082569964.72378.732879995.08973.7342810008.0172.6209810028.6774.52145
10061.2475.2914610113.4878.6926910150.8879.7301810194.6681.9353310221.4484.11012
10241.3884.72638 10284.589.0684510343.9389.7270810373.6191.6509110393.3990.84346
10403.2692.5031310442.7492.1517110472.3494.4725710488.7994.0565910500.9394.97418
#Mann= 3 , 0 , 0
9499.044  0.1043       09499.044  0.1043       010500.93  0.1043       0
#XS Ineff= 2 , 0
       0                               0
Bank Sta=9499.044,10500.93
Exp/Cntr=0.3,0.1