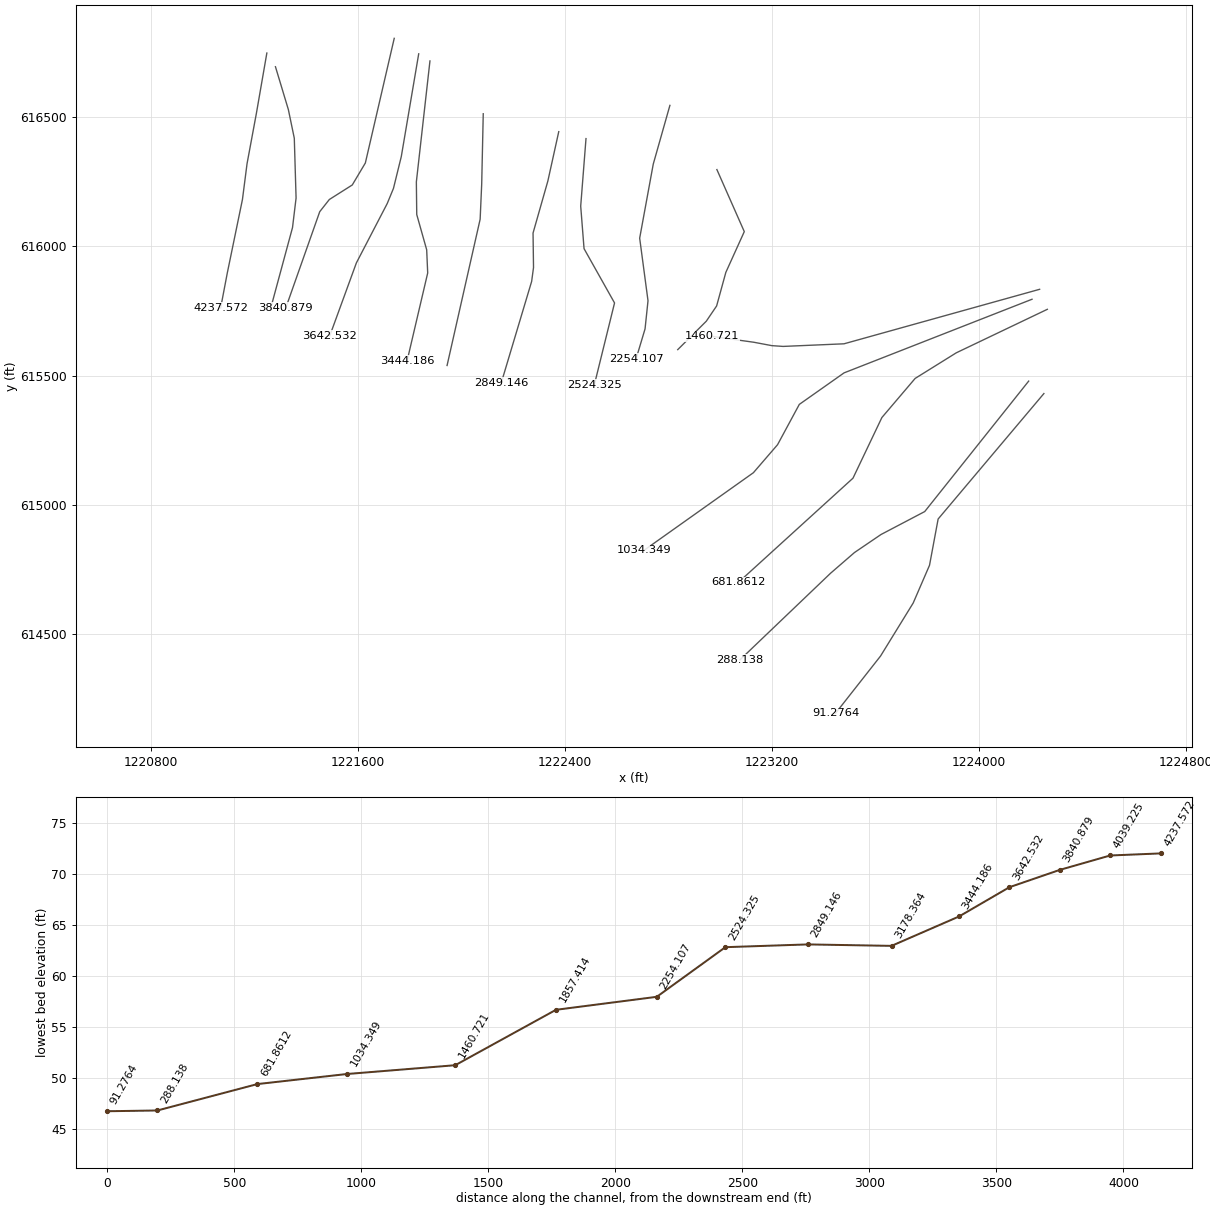
HEC-RAS study 241_ras.prj: 241

--- 241_ras.g01 (geometry) --- (continued)

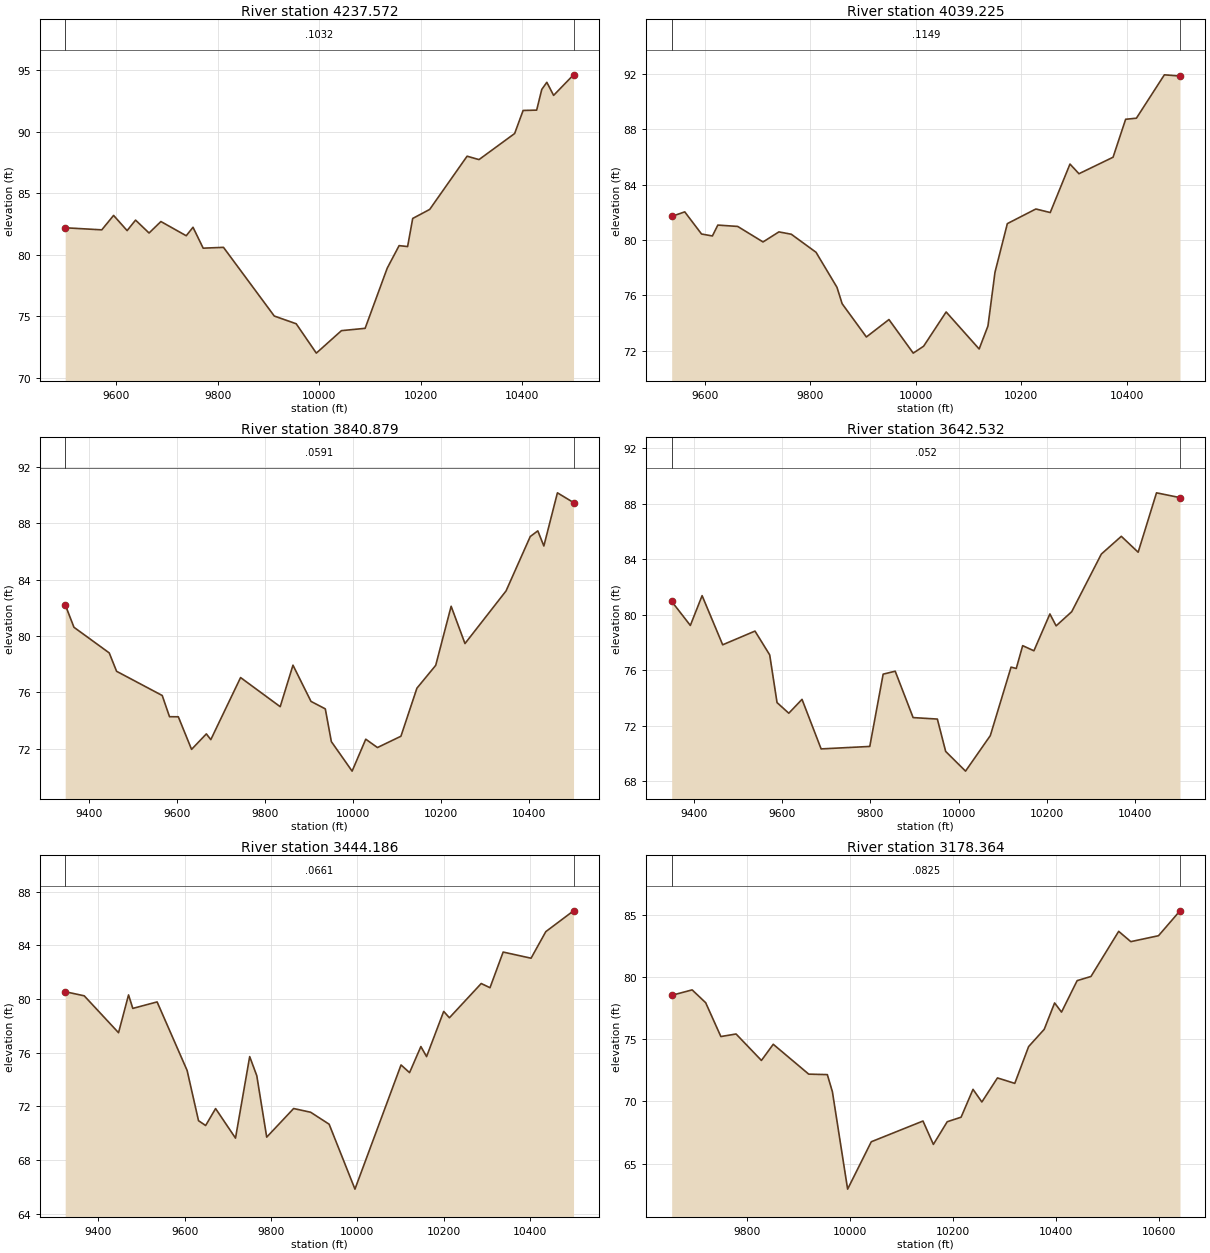
Type RM Length L Ch R = 1 ,4237.572,198.346500,198.346500,198.346500
XS GIS Cut Line= 6
1221247.47039523616746.9285462921221206.94469386616513.278391627
1221170.88261397616319.0069373481221153.19596005  616181.2084005
1221094.70369874615897.4244900631221068.78911643615761.354431167
#Sta/Elev= 30
9499.00982.200719571.08982.031989594.39883.204519621.03681.971219637.68682.82217
9664.32481.775229687.63382.707349737.58381.553429750.93182.241729770.95280.54498
9810.99480.610959911.10175.035549954.348 74.40699993.99672.0236710043.5473.84942
10090.1974.0367410133.7478.9215810157.1880.7500310173.9380.6760410183.98 82.9569
10217.4883.6909810291.1888.0114510314.6387.73439 10384.989.85233 10401.691.72426
10428.3291.7516910438.3493.4280710448.3694.0106810461.7292.9494310500.9894.61765
#Mann= 3 , 0 , 0
9499.009  0.1032       09499.009  0.1032       010500.98  0.1032       0
#XS Ineff= 2 , 0
       0                               0
Bank Sta=9499.009,10500.98
Exp/Cntr=0.3,0.1

Type RM Length L Ch R = 1 ,4039.225,198.346500,198.346500,198.346500
XS GIS Cut Line= 6
 1221280.6930609616694.0562857541221330.63449651616528.250719607
1221353.53859335616417.6129359011221360.41833848616186.516435444
 1221346.6373421616072.4070020471221260.30148497  615753.0617771
#Sta/Elev= 30
9537.38281.705269562.18182.036089594.02680.433929614.58580.293559624.86481.08029
9662.55580.982629710.54679.860539740.67980.588019764.13280.418459811.03779.11252
9850.69476.581889860.54775.391249906.48672.988069949.25174.248469995.28871.81992
10014.9972.3204610057.6774.7969610120.2472.1193310136.9373.7843110150.2877.67073
10173.6981.1858110227.7782.2446310254.9981.9872310292.42 85.494310309.4484.79403
10374.0985.9878810397.9188.7317510418.3388.8109510471.3491.9471310500.9691.85858
#Mann= 3 , 0 , 0
9537.382  0.1149       09537.382  0.1149       010500.96  0.1149       0
#XS Ineff= 2 , 0
       0                               0
Bank Sta=9537.382,10500.96
Exp/Cntr=0.3,0.1

Type RM Length L Ch R = 1 ,3840.879,198.346400,198.346400,198.346400
XS GIS Cut Line= 6
1221739.73671997616803.7335852941221628.11401686616321.985782666
1221577.59817152 616237.069509451221488.86701947616180.842471261
1221451.86392391616133.8660611791221320.49553363615761.611501296
#Sta/Elev= 30
9345.27782.223269365.19580.618459445.38878.799329462.09477.494449565.84875.77693
9582.38374.272289602.431 74.26629632.51171.952579666.15273.052049676.24472.64295
9743.93677.050349833.99874.982989863.05577.928989903.96975.35956 9936.5274.82778
  9950.372.503339997.48970.4091410028.5172.6747610055.1172.0825710108.4372.88541
10144.7876.2947910187.5277.91565 10222.682.1105310254.07 79.463610347.4583.19966
10402.4987.0631610419.6387.4627510433.3586.3889610464.2190.1621510500.8289.47189
#Mann= 3 , 0 , 0
9345.277  0.0591       09345.277  0.0591       010500.82  0.0591       0
#XS Ineff= 2 , 0
       09882.281                       0
Bank Sta=9345.277,10500.82
Exp/Cntr=0.3,0.1

Type RM Length L Ch R = 1 ,3642.532,198.346500,198.346500,198.346500
XS GIS Cut Line= 6
 1221834.3251333616743.8565163171221767.02832456616346.873984846
1221736.76723491616223.8059504631221712.65527353616165.274543097
 1221593.4123589615935.7974088321221490.75648294615654.398981682
#Sta/Elev= 30
9349.75380.948449392.04979.21592 9418.6781.363319465.25777.819919538.46578.80815
9571.74277.09319 9588.3873.653829615.00172.88692 9644.9573.888329688.20970.31496
 9798.4170.493069828.67575.703429855.98675.915259896.53472.57293 9951.4372.46607
9970.26570.1330810015.2468.7133410071.3471.2724710118.3476.2089910130.1276.11278
10144.6577.7577710170.0977.3877210206.2880.04295 10220.479.1841710255.7280.20573
10322.8184.3607710368.0485.6399610406.1584.4925910447.7288.7746610500.9288.42954
#Mann= 3 , 0 , 0
9349.753   0.052       09349.753   0.052       010500.92   0.052       0
#XS Ineff= 2 , 0
       09848.452                       0
Bank Sta=9349.753,10500.92
Exp/Cntr=0.3,0.1

Type RM Length L Ch R = 1 ,3444.186,265.821700,265.821700,265.821700
XS GIS Cut Line= 6
 1221877.7877859616716.343461008   1221825.23066616248.790871951
1221826.74145607616122.7928661141221865.15241668615986.478578079
1221869.05342915615896.9301195561221789.59296751615557.790136192
#Sta/Elev= 30
9323.29980.542269367.40480.235459446.84777.489389470.01880.302079479.94879.29939
 9536.2279.781889605.73274.677729632.12870.940659648.61570.581619671.69671.84316
9717.81269.642539750.673 75.71229767.104 74.29079790.10769.71665 9852.4571.84542
9891.834 71.56949934.709 70.67839994.52665.8458310101.2975.09011   1012174.51743
10147.2576.4599510160.4475.7116910200.1279.0757110213.35 78.602410287.0381.15172
10307.3580.8395410337.8383.4933210402.4883.0351110436.6485.0130210500.87 86.5627
#Mann= 3 , 0 , 0
9323.299  0.0661       09323.299  0.0661       010500.87  0.0661       0
#XS Ineff= 2 , 0
       09745.882                       0
Bank Sta=9323.299,10500.87
Exp/Cntr=0.3,0.1

Type RM Length L Ch R = 1 ,3178.364,329.217800,329.217800,329.217800
XS GIS Cut Line= 4
 1222083.7513451616512.2694602161222077.75837281616240.588050634
1222071.76540053616104.7473458951221943.91532546615539.410295099
#Sta/Elev= 30
9653.87478.513729693.65678.952349719.90977.923789749.44475.208049778.97975.41361
9828.20373.290339851.17474.588449920.08972.192689956.20972.154279966.06170.78142
9995.61762.9666410041.59 66.766710142.0268.43039 10162.266.5557310189.11  68.374
10216.0268.7385410239.1870.9729810256.3869.9570610286.6671.8893110320.2971.45155
 10347.274.4042410377.4875.7865910397.6677.9044310411.1177.1699610441.3979.69245
 10468.380.0295310522.12 83.649910545.6682.8228410599.48 83.298710641.2185.29538
#Mann= 3 , 0 , 0
9653.874  0.0825       09653.874  0.0825       010641.21  0.0825       0
#XS Ineff= 2 , 0
       0                               0
Bank Sta=9653.874,10641.21
Exp/Cntr=0.3,0.1

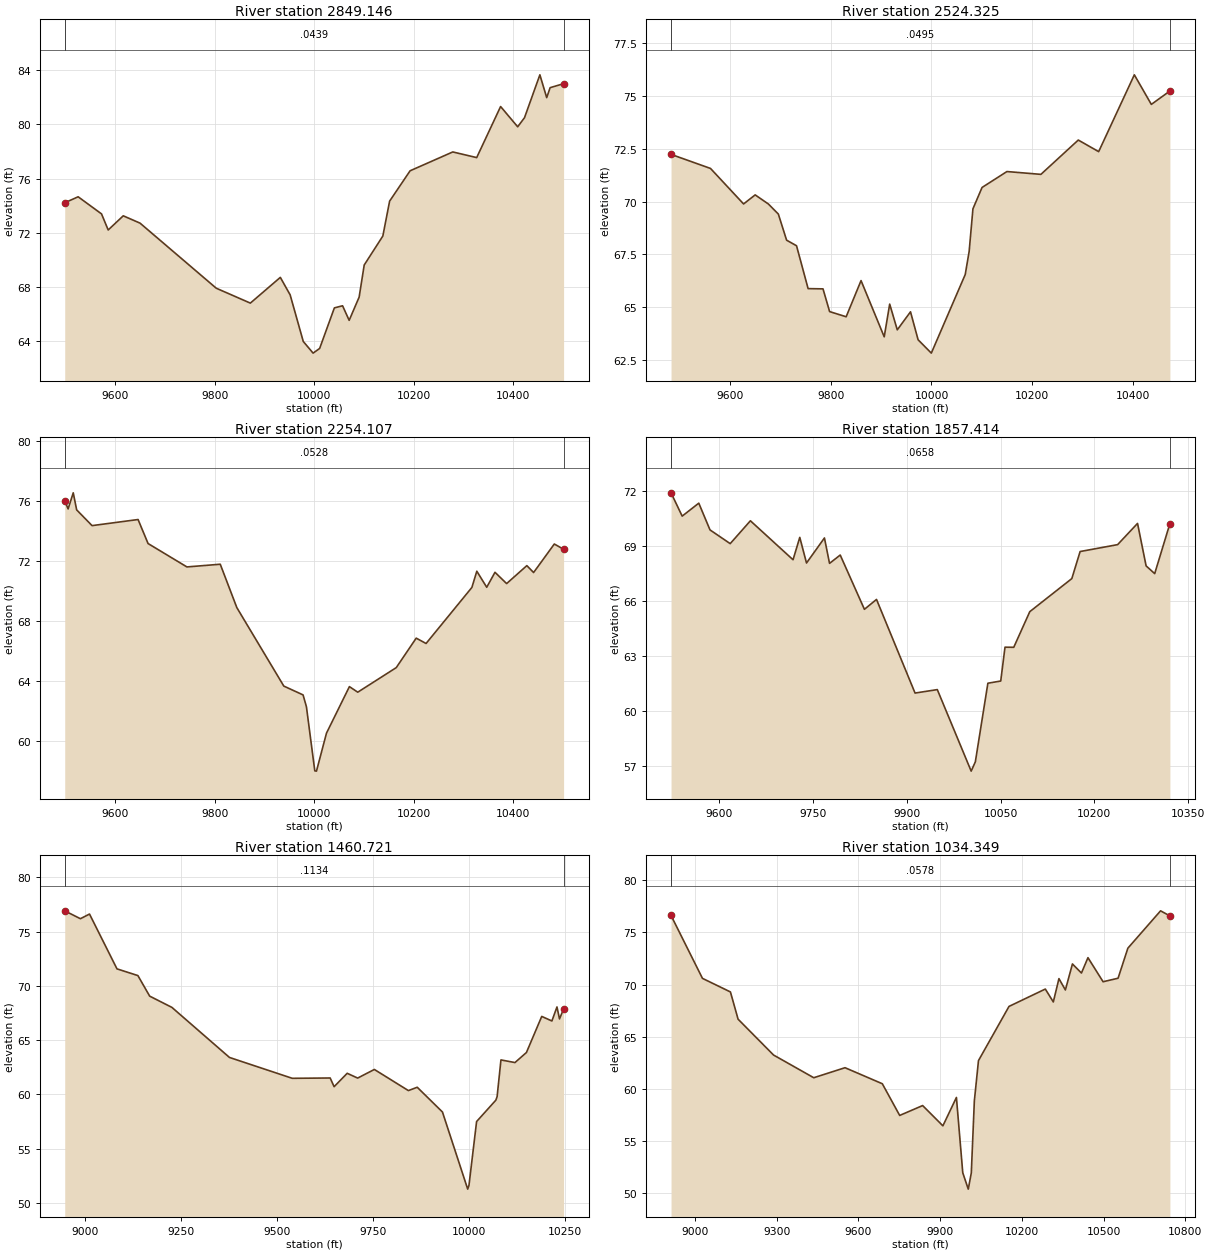
Type RM Length L Ch R = 1 ,2849.146,324.820800,324.820800,324.820800
XS GIS Cut Line= 6
 1222375.5368487616443.0964420871222333.50224887616252.603647616
1222276.19862951616051.3003046171222278.01700322615917.978850805
1222270.78485516615864.3483998151222153.30548338615472.196591234
#Sta/Elev= 30
9499.07374.217179526.02174.657599572.95273.394369586.36172.206699616.59273.25182
9650.28372.713069803.36467.904199871.84166.803819932.05368.704889951.76567.41423
 9978.1263.972029997.88663.1093510011.0363.45633 10040.666.4516410057.0666.60682
10070.3165.5318610090.3467.2476410100.5269.6190610137.9371.7581110151.5374.33638
10192.6876.5785710278.4177.9705310326.4277.5529710374.4381.3246810408.7279.82951
10422.4480.50053 10453.383.6674810467.0281.9812110473.8882.7186410500.9483.01323
#Mann= 3 , 0 , 0
9499.073  0.0439       09499.073  0.0439       010500.94  0.0439       0
#XS Ineff= 2 , 0
       0                               0
Bank Sta=9499.073,10500.94
Exp/Cntr=0.3,0.1

Type RM Length L Ch R = 1 ,2524.325,270.218600,270.218600,270.218600
XS GIS Cut Line= 5
1222480.82291713616416.2459699391222460.37094411616155.327593282
1222473.29454267615990.8808727561222591.15633059615781.126843303
1222513.24769112615465.496970415
#Sta/Elev= 30
9481.97472.229859560.47771.564889626.29569.886689649.33270.315879675.65969.88398
9695.40469.410119711.85968.176099731.60467.911949754.64165.887049784.25965.87536
9797.42364.801139830.33264.557119859.95166.266069906.02463.609049916.93865.15531
9931.99163.938799958.33464.79097 9973.4463.47076 9999.7362.83915 10067.266.55344
   10075 67.646310082.5269.6583310100.6970.6666210150.1671.4184310217.7471.28528
10292.0972.9064210332.6472.3591310403.6175.98819 10437.474.5905610474.3575.22496
#Mann= 3 , 0 , 0
9481.974  0.0495       09481.974  0.0495       010474.35  0.0495       0
#XS Ineff= 2 , 0
       0                               0
Bank Sta=9481.974,10474.35
Exp/Cntr=0.3,0.1

Type RM Length L Ch R = 1 ,2254.107,396.692900,396.692900,396.692900
XS GIS Cut Line= 6
1222805.07418696616544.6189284211222740.77727131616317.769894977
1222688.25536659616031.3975238141222720.47736624615789.602208185
1222709.05808998615680.9108090541222674.57411124615565.818030919
#Sta/Elev= 30
9499.04776.00207 9505.8575.454929516.14476.527559523.007 75.39119553.88974.34127
9646.33874.747799666.40473.146539744.403 71.58789811.353 71.76779844.66768.87459
9938.97663.645029977.65663.056849984.38162.2687510001.2157.9939510004.5657.97613
10024.65 60.506510070.7263.6091810087.4863.2380810164.7964.8759810204.83 66.8404
10224.6866.4848110316.6570.2203310326.5571.3019310346.4570.2321810363.0471.23011
10386.3970.4779310427.0271.6741410440.5771.2146210482.1773.1146510500.81 72.7663
#Mann= 3 , 0 , 0
9499.047  0.0528       09499.047  0.0528       010500.81  0.0528       0
#XS Ineff= 2 , 0
       0                               0
Bank Sta=9499.047,10500.81
Exp/Cntr=0.3,0.1

Type RM Length L Ch R = 1 ,1857.414,396.693000,396.693000,396.693000
XS GIS Cut Line= 6
1222986.69250044616296.5224584941223092.56834385616056.803567708
1223021.26908113615899.3173606771222985.64491179615769.545730276
1222945.64958361615710.5016237971222835.35632144615600.669356122
#Sta/Elev= 30
 9523.4871.906319541.26670.63355 9567.82 71.34179585.75369.881359618.03269.13066
9650.311 70.37939718.45668.250619729.21669.472839739.976 68.07269768.64269.44094
9776.76368.05222 9793.8668.507699832.51765.543619851.84166.083529913.44660.96946
 9949.01 61.157610003.1356.7051610009.8157.2147510029.8361.5068710050.36 61.6269
10057.21 63.4743 10071.263.46912 10096.865.4150510163.9867.2211110177.2468.69934
10237.1769.0764910269.0170.2356210282.7267.9154510296.4367.4928110320.7470.22632
#Mann= 3 , 0 , 0
 9523.48  0.0658       0 9523.48  0.0658       010320.74  0.0658       0
#XS Ineff= 2 , 0
       0                               0
Bank Sta=9523.48,10320.74
Exp/Cntr=0.3,0.1

Type RM Length L Ch R = 1 ,1460.721,426.372500,426.372500,426.372500
XS GIS Cut Line= 6
1224233.84148991615833.8457360591223477.85541221615623.226973059
 1223242.5905235615613.1201405511223198.81166775615616.147344728
1223129.04906578615629.2956579991222966.87771021615651.956007274
#Sta/Elev= 30
8946.75976.916078987.574 76.1892 9011.2776.618399082.79171.569199137.283 70.9508
9167.93569.056789225.83468.019659375.68863.408269539.16661.486239637.933 61.5154
9648.151 60.71449682.20861.947579709.45561.507739752.93562.30159  9841.660.35439
9864.58760.662539930.26458.380969995.99851.277289999.28351.6219610019.1457.50266
10069.2159.4695910072.5559.7940110082.5663.1810710119.07 62.936710148.9363.86465
10188.7567.1880310215.2166.7686110228.4268.0595510235.0266.9581910245.6867.86662
#Mann= 3 , 0 , 0
8946.759  0.1134       08946.759  0.1134       010245.68  0.1134       0
#XS Ineff= 2 , 0
       0                               0
Bank Sta=8946.759,10245.68
Exp/Cntr=0.3,0.1

Type RM Length L Ch R = 1 ,1034.349,352.487300,352.487300,352.487300
XS GIS Cut Line= 6
1224204.51223731615795.395464882 1223478.2585533615510.965392545
1223305.15890047615389.0274985581223221.12352633615233.313913375
1223127.73222604 615125.054163531222705.66642907614825.534674257
#Sta/Elev= 30
8912.37976.612079027.69670.590299130.32769.290719158.44866.68277 9288.5163.25346
9436.148 61.07819550.89562.038429687.75860.503389751.50557.46885 9835.7858.41514
9910.064 56.47359959.72359.190369983.02351.9797910003.2450.4152610014.3751.97272
10025.5358.86404 10040.762.7194910152.7267.9047310285.97 69.567610315.3468.33432
10335.9770.5648310359.6169.48104 10385.571.9699610418.5271.0992810442.4872.57149
10498.0370.2669310553.0170.6043410588.9373.4787610708.9677.0557310743.2276.56808
#Mann= 3 , 0 , 0
8912.379  0.0578       08912.379  0.0578       010743.22  0.0578       0
#XS Ineff= 2 , 0
       0                               0
Bank Sta=8912.379,10743.22
Exp/Cntr=0.3,0.1

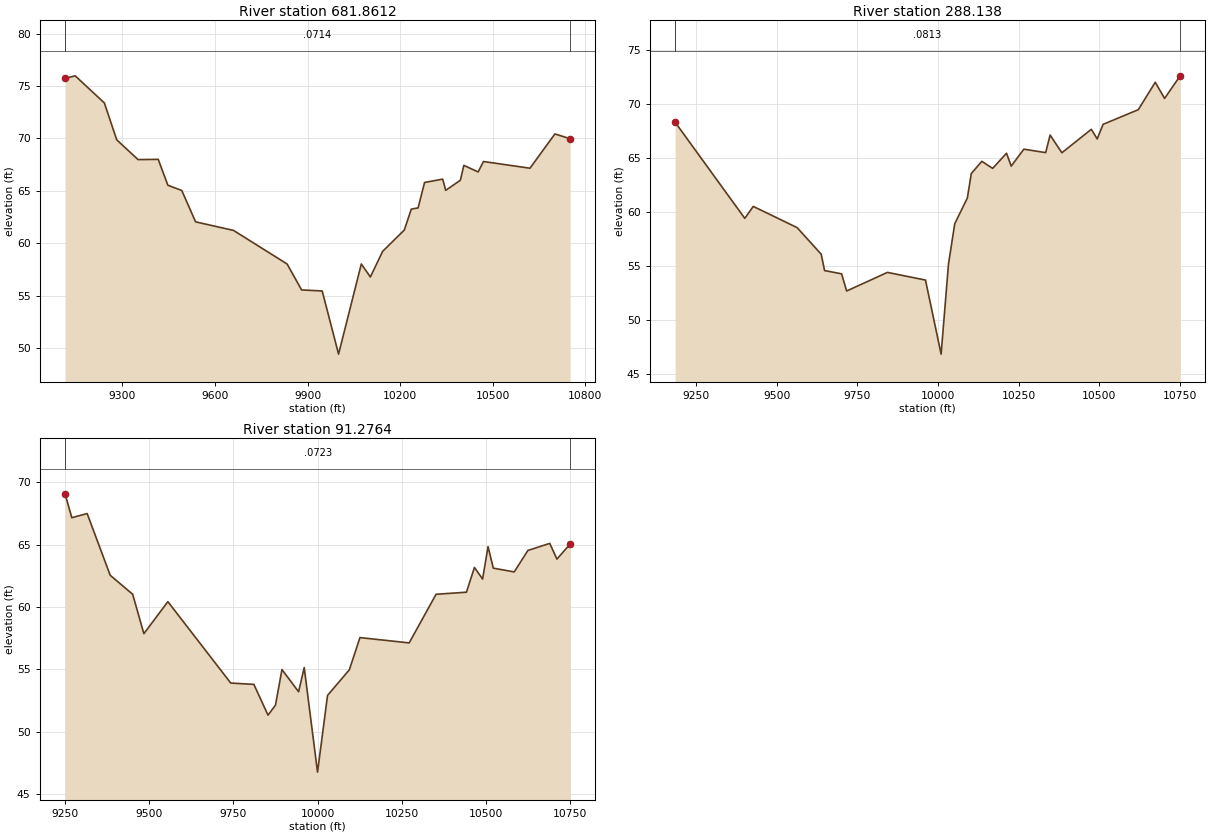
Type RM Length L Ch R = 1 ,681.8612,393.723200,393.723200,393.723200
XS GIS Cut Line= 6
1224263.71284062615756.5450689641223911.84091604615588.443012208
1223752.84240952615489.4489714651223624.33329082615338.340716705
1223512.62494728615103.9303543721223069.79785803614701.198059902
#Sta/Elev= 30
9114.272 75.72329147.16475.96807  9241.773.381889281.69669.869569350.78167.98012
9416.22968.002449447.45865.534189492.58565.032289537.193 62.04419660.21861.22628
9833.86658.023059880.796 55.55069947.51455.4532510000.5749.4298310074.2658.02532
10103.6456.7855110143.4459.2332410213.6661.2664610236.1363.2526610258.2563.37414
10279.2465.7983810337.9766.1174210347.7665.0480710395.3166.0134510406.49  67.431
10452.7966.8008910470.1167.7981410620.7767.1577610701.6270.4276310750.9269.97104
#Mann= 3 , 0 , 0
9114.272  0.0714       09114.272  0.0714       010750.92  0.0714       0
#XS Ineff= 2 , 0
       0                               0
Bank Sta=9114.272,10750.92
Exp/Cntr=0.3,0.1

Type RM Length L Ch R = 1 , 288.138,196.861600,196.861600,196.861600
XS GIS Cut Line= 6
1224191.56210536615479.0422409031223789.81214893614974.887803108
1223620.95832393614886.2668819131223518.36541036614816.583780825
1223425.90775526 614736.523898811223076.10953707614402.174090937
#Sta/Elev= 30
9185.10268.327759401.23259.417059427.55460.523459563.47958.559619638.13256.09518
9648.66154.580459701.30654.279519717.09952.689179843.35354.411839961.39853.70255
 10009.946.8434810032.7555.1869610052.14  58.91610091.2561.3018710103.4563.56385
   1013664.70106 10169.764.0426110212.5765.4484410227.2464.2550210266.4165.82402
10334.0365.5045310347.7267.1311710384.2465.4900510475.51 67.661310493.7766.77246
10512.0268.1236410621.1769.4800110673.7672.0201910702.6370.5212110750.9372.61559
#Mann= 3 , 0 , 0
9185.102  0.0813       09185.102  0.0813       010750.93  0.0813       0
#XS Ineff= 2 , 0
       0                               0
Bank Sta=9185.102,10750.93
Exp/Cntr=0.3,0.1

Type RM Length L Ch R = 1 , 91.2764,0.000000,0.000000,0.000000
XS GIS Cut Line= 6
1224250.36933743615430.9482031661223841.68818125614946.185367655
 1223808.4171523614767.4198974251223745.26985427 614621.44370693
1223619.12945056614416.5675167971223444.90437165614195.001613082
#Sta/Elev= 30
9249.20769.064199269.36467.150969314.95367.48445  9383.462.54294 9450.3361.01588
9483.56657.861999554.90860.425939741.89353.90494 9810.6153.797929852.60551.33592
9874.867 52.13459894.07554.987239943.59653.209879960.29755.144879999.872 46.7693
10029.5952.9132510094.4754.9692510125.9757.54758 10272.357.1211610352.31 61.0175
10442.5761.1824510466.3763.1666510490.5762.2378410506.77 64.831210522.4763.10967
10584.72 62.8076 10625.264.5274610690.2765.0922210711.63 63.837310750.8765.04169
#Mann= 3 , 0 , 0
9249.207  0.0723       09249.207  0.0723       010750.87  0.0723       0
#XS Ineff= 2 , 0
       0                               0
Bank Sta=9249.207,10750.87
Exp/Cntr=0.3,0.1